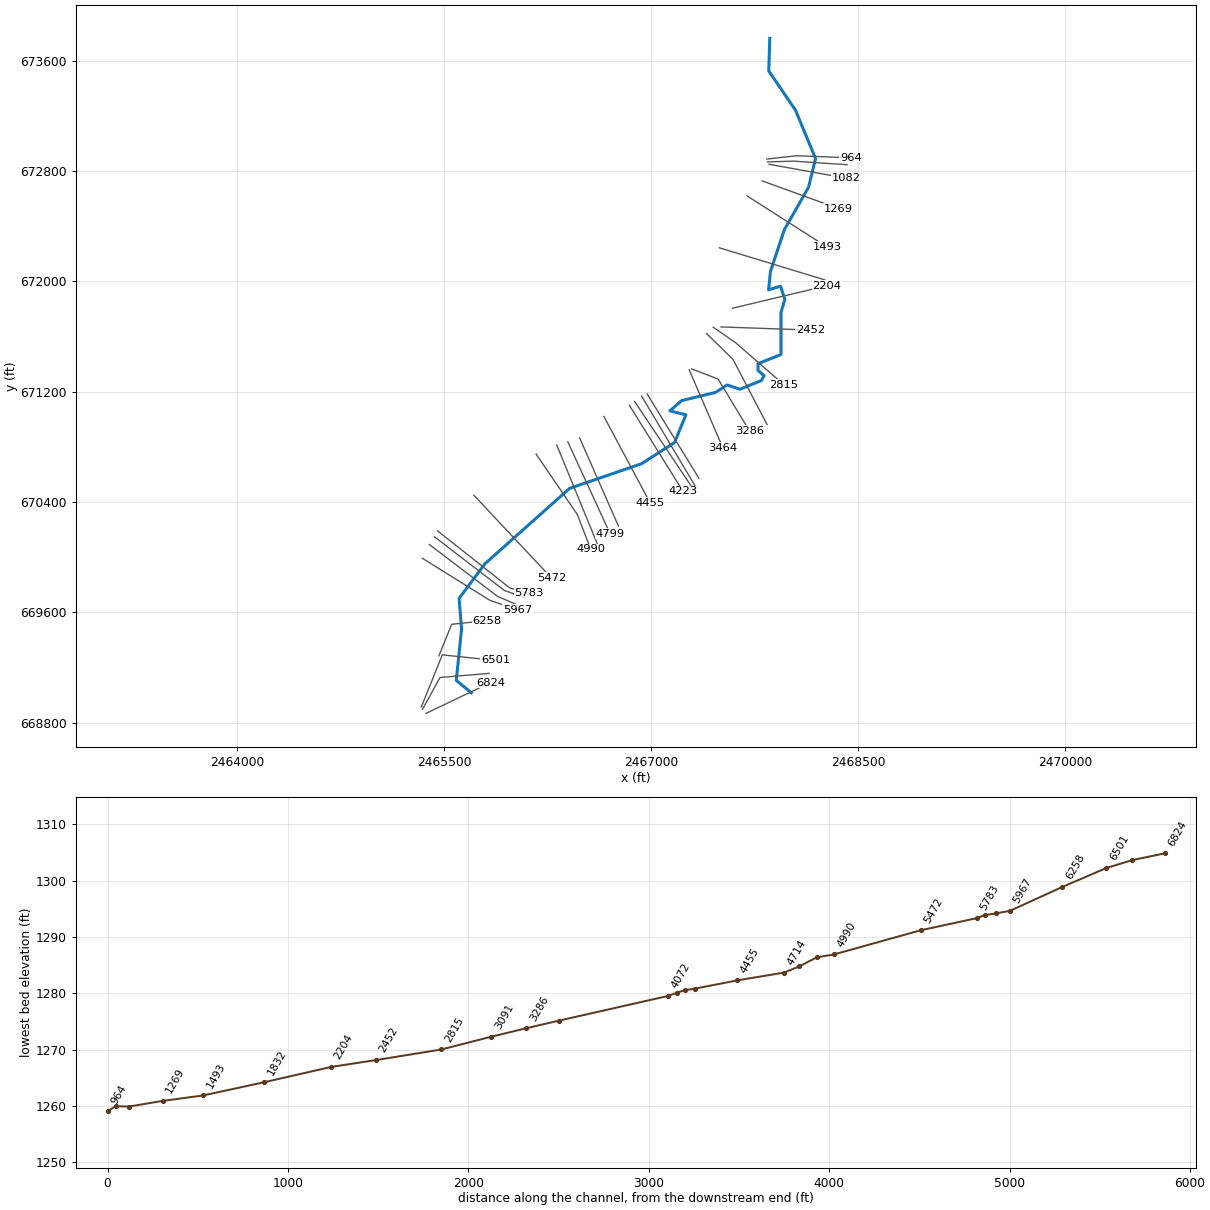
--- STONYCK_T1.prj (project) ---

Proj Title=STONYCK_T1
Current Plan=p01
Default Exp/Contr=0,0
English Units
Geom File=g01
Flow File=f01
Plan File=p01
BEGIN DESCRIPTION:
Stream Name: Stony Creek
Flood Zone: Approximate
Pendleton County, West Virginia
HEC-RAS Version: 5.0.7
Hydrology Method:
Regression equation
END DESCRIPTION:
DSS Export Rating Curves= 0
DSS Export Rating Curve Sorted= 0
DSS Export Volume Flow Curves= 0
DXF Filename=H:\CTP\WV\f03_Pendleton_RiskMAP\f05_Engineering\f02_Hydraulics\02_Final\Approximate\STONYCK_T1\STONYCK_T1.
DXF OffsetX= 0
DXF OffsetY= 0
DXF ScaleX= 0
DXF ScaleY= 0

--- STONYCK_T1.p01 (plan) ---

Plan Title=Floodplain
Program Version=5.07
Short Identifier=Floodplain
Geom File=g01
Flow File=f01
Subcritical Flow
K Sum by GR= 0
Std Step Tol= 0.01
Critical Tol= 0.01
Num of Std Step Trials= 20
Max Error Tol= 0.3
Flow Tol Ratio= 0.001
Split Flow NTrial= 30
Split Flow Tol= 0.02
Split Flow Ratio= 0.02
Log Output Level= 0
Friction Slope Method= 1
Unsteady Friction Slope Method= 2
Unsteady Bridges Friction Slope Method= 1
Parabolic Critical Depth
Global Vel Dist= 0 , 0 , 0
Global Log Level= 0
CheckData=True
Encroach Param=-1 ,0,0, 0
Mapping Interval=1HOUR
Computation Time Step Use Courant=        0
Computation Time Step Use Time Series=    0
Computation Time Step Count To Double=0
Computation Time Step Max Doubling=0
Computation Time Step Max Halving=0
Computation Time Step Residence Courant=0
Run HTab= 0
Run UNet= 0
Run Sediment= 0
Run PostProcess= 0
Run WQNet= 0
Run RASMapper= 0
UNET Theta= 0
UNET Theta Warmup= 0
UNET ZTol= 0
UNET ZSATol= 0
UNET MxIter= 0
UNET Max Iter WO Improvement= 0
UNET MaxInSteps= 0
UNET DtIC= 0
UNET DtMin= 0
UNET MaxCRTS= 0
UNET WFStab= 0
UNET SFStab= 0
UNET WFX= 1
UNET SFX= 1
UNET 1D Methodology=Finite Difference
UNET DSS MLevel= 1
UNET Pardiso=0
UNET DZMax Abort= 0
UNET Use Existing IB Tables= 0
UNET Froude Reduction=False
UNET Froude Limit= 0
UNET Froude Power= 0
UNET D1 Cores= 0
UNET D2 Coriolis=0
UNET D2 Cores= 0
UNET D2 Theta= 1
UNET D2 Theta Warmup= 1
UNET D2 Z Tol= 0.01
UNET D2 Volume Tol= 0.01
UNET D2 Max Iterations= 20
UNET D2 Equation= 0
UNET D2 RampUpFraction=0.1
UNET D2 TimeSlices= 1
UNET D2 BCVolumeCheck=0
UNET D1D2 MaxIter= 0
UNET D1D2 ZTol=0.01
UNET D1D2 QTol=0.1
UNET D1D2 MinQTol=1
Write IC File= 0
Write IC File at Fixed DateTime=0
Write IC File at Sim End=0
Echo Input=False
Echo Parameters=False
Echo Output=False
Write Detailed= 0
HDF Write Warmup=0
HDF Write Time Slices=0
HDF Flush=0
HDF Face Node Velocities=0
HDF Compression= 1
HDF Chunk Size= 1
HDF Spatial Parts= 1
HDF Use Max Rows=0
HDF Fixed Rows= 1
Calibration Method= 0
Calibration Iterations= 20
Calibration Max Change=0.05
Calibration Tolerance=0.2
Calibration Maximum=1.5
Calibration Minimum=0.5
Calibration Optimization Method= 1
WQ AD Non Conservative
WQ ULTIMATE=-1
WQ Max Comp Step=1HOUR
WQ Output Interval=15MIN
WQ Output Selected Increments= 0
WQ Output face flow=0
WQ Output face velocity=0
WQ Output face area=0
WQ Output face dispersion=0
WQ Output cell volume=0
WQ Output cell surface area=0
WQ Output cell continuity=0
WQ Output cumulative cell continuity=0
WQ Output face conc=0
WQ Output face dconc_dx=0
WQ Output face courant=0
WQ Output face peclet=0
WQ Output face adv mass=0
WQ Output face disp mass=0
WQ Output cell mass=0
WQ Output cell source sink temp=0
WQ Output nsm pathways=0
WQ Output nsm derived pathways=0
WQ Output MaxMinRange=-1
WQ Daily Max Min Mean=-1
WQ Daily Range=0
WQ Daily Time=0
WQ Create Restart=0
WQ Fixed Restart=0
WQ System Summary=0
WQ Write To DSS=0
WQ Use Fixed Temperature=0
Sorting and Armoring Iterations= 10
XS Update Threshold= 0.02
Bed Roughness Predictor= 0
Hydraulics Update Threshold= 0.02
Energy Slope Method= 1
Volume Change Method= 1
Sediment Retention Method= 0
XS Weighting Method= 0
Number of US Weighted Cross Sections= 1
Number of DS Weighted Cross Sections= 1
Upstream XS Weight=0
Main XS Weight=1
Downstream XS Weight=0
Number of DS XS's Weighted with US Boundary= 1
Upstream Boundary Weight= 1
Weight of XSs Associated with US Boundary= 0
Number of US XS's Weighted with DS Boundary= 1
Downstream Boundary Weight= 0.5
Weight of XSs Associated with DS Boundary= 0.5
Percentile Method= 0
Sediment Output Level= 3
Mass or Volume Output= 0
Output Increment Type= 1
Profile and TS Output Increment= 1
XS Output Flag= 0
XS Output Increment= 10
Write Gradation File= 0
Read Gradation Hotstart= 0
Write HDF5 File= 1
Write Binary Output= 1
Write DSS Sediment File= 0
SV Curve= 0
Specific Gage Flag= 0

--- STONYCK_T1.f01 (steady flow) ---

Flow Title=Flows
Program Version=5.07
Number of Profiles= 6
Profile Names=P100yr,P10yr,P25yr,P50yr,P500yr,P101yr
River Rch & RM=STONYCK,Main            ,6824
     559     262     370     462     820     681
River Rch & RM=STONYCK,Main            ,5783
    1087     504     715     895    1604    1323
River Rch & RM=STONYCK,Main            ,3286
    1324     612     869    1090    1958    1611
River Rch & RM=STONYCK,Main            ,0
    2918    1311    1890    2388    4378    3618
River Rch & RM=STONYCK_T1,Main            ,986
     560     262     370     462     820     681
Boundary for River Rch & Prof#=STONYCK,Main            , 1
Up Type= 0
Dn Type= 1
Dn Known WS=1259.25
Boundary for River Rch & Prof#=STONYCK,Main            , 2
Up Type= 0
Dn Type= 1
Dn Known WS=1257.33
Boundary for River Rch & Prof#=STONYCK,Main            , 3
Up Type= 0
Dn Type= 1
Dn Known WS=1258.21
Boundary for River Rch & Prof#=STONYCK,Main            , 4
Up Type= 0
Dn Type= 1
Dn Known WS=1258.93
Boundary for River Rch & Prof#=STONYCK,Main            , 5
Up Type= 0
Dn Type= 1
Dn Known WS=1259.93
Boundary for River Rch & Prof#=STONYCK,Main            , 6
Up Type= 0
Dn Type= 1
Dn Known WS=1259.58
Boundary for River Rch & Prof#=STONYCK_T1,Main            , 1
Up Type= 0
Dn Type= 3
Dn Slope=0.01405
Boundary for River Rch & Prof#=STONYCK_T1,Main            , 2
Up Type= 0
Dn Type= 3
Dn Slope=0.01405
Boundary for River Rch & Prof#=STONYCK_T1,Main            , 3
Up Type= 0
Dn Type= 3
Dn Slope=0.01405
Boundary for River Rch & Prof#=STONYCK_T1,Main            , 4
Up Type= 0
Dn Type= 3
Dn Slope=0.01405
Boundary for River Rch & Prof#=STONYCK_T1,Main            , 5
Up Type= 0
Dn Type= 3
Dn Slope=0.01405
Boundary for River Rch & Prof#=STONYCK_T1,Main            , 6
Up Type= 0
Dn Type= 3
Dn Slope=0.01405
DSS Import GetInterval= 0
DSS Import GetPeak= 0
DSS Import FillOption= 0

--- STONYCK_T1.g01 (geometry) ---

Geom Title=Geometry
Program Version=5.07

River Reach=STONYCK         ,Main
Reach XY= 30
2465695.72400001669015.709000021     2465586.824 669106.21100001
2465625.09100002669479.2530000212465607.01400003669700.605000004
2465794.51800001669951.868000016     2466408.285670499.069000021
2466930.20900002670677.800999999     2467168.792670831.670000002
2467250.86300004671032.464000016     2467134.877671061.148000017
2467219.59700003671135.3460000012467465.67199999671194.998999998
2467549.26700002671249.0090000032467642.87400001671217.932999998
2467797.68700001671281.3579999952467817.99700004671315.691000015
2467773.33800003671355.3490000072467773.43900004671403.292000011
        2467940.671469.6969999972467939.87800002671773.839000016
2467968.44400004671871.138999999     2467936.574671965.682000011
     2467850.391671939.0500000122467863.87900001672072.917000011
2467965.73600003672377.7950000022468139.66299999672682.418000013
2468190.68200004672891.4239999952468046.09999999673241.138999999
2467851.69800001673526.8960000132467858.90970787673763.631603837

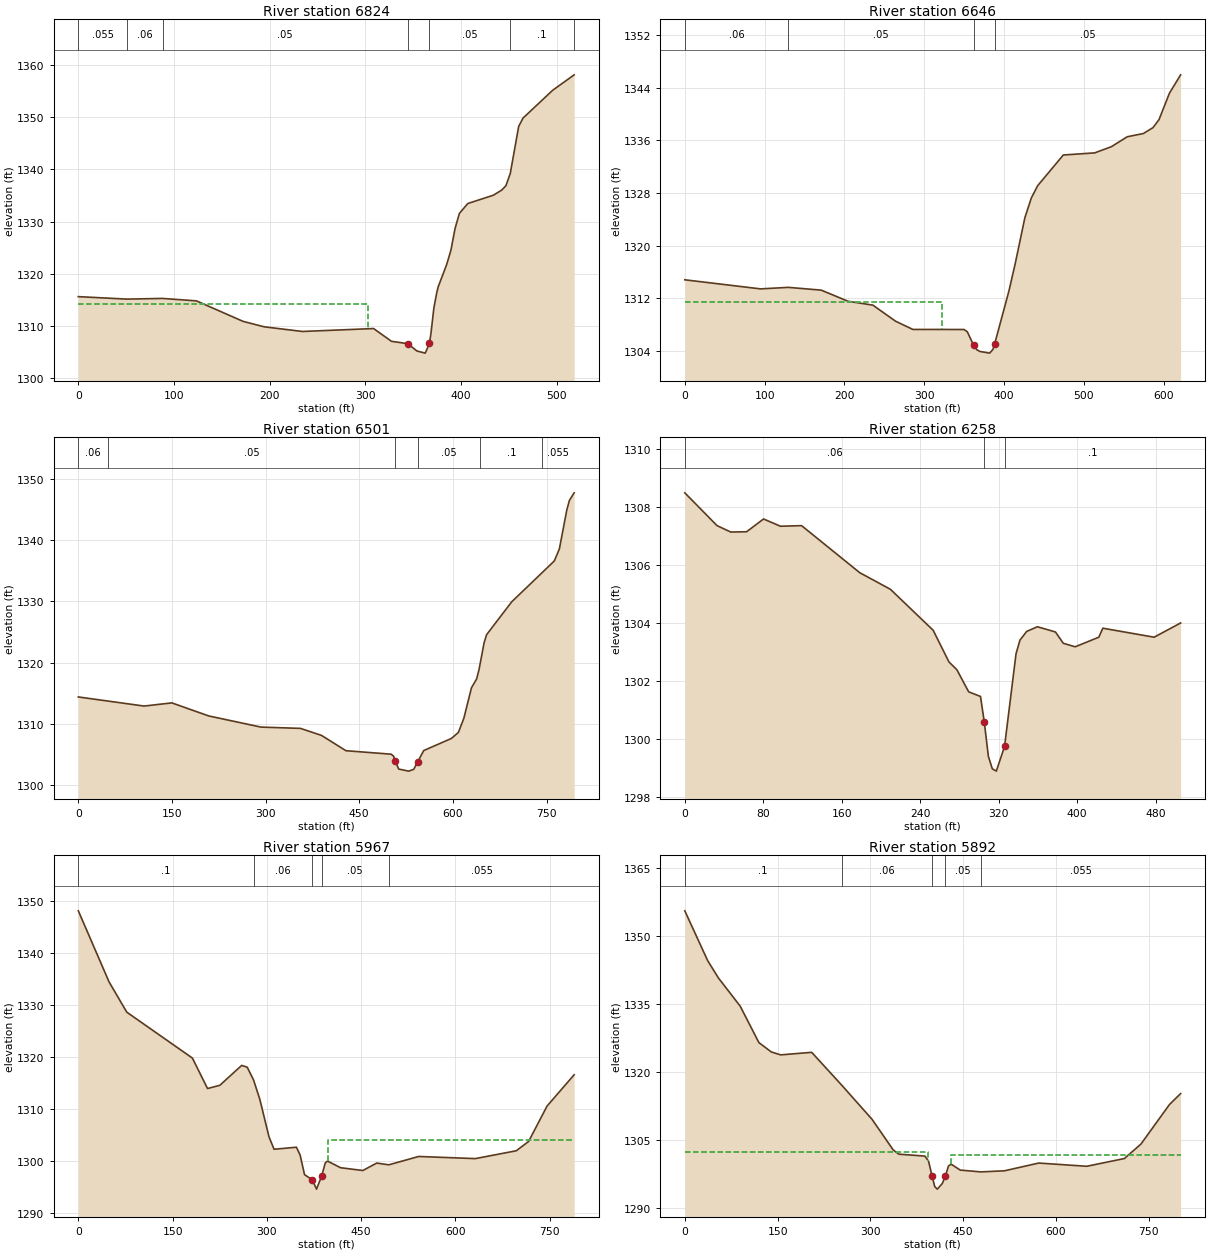
Type RM Length L Ch R = 1 ,6824    ,183.8,177.9,170.8
XS GIS Cut Line= 2
2465367.34315811668866.6335242742465835.03110654669090.242403714
#Sta/Elev= 30
       0 1315.65    50.7 1315.18      88 1315.31   123.5 1314.84   172.3 1310.92
   194.4 1309.88   234.3 1308.99   308.7 1309.55   327.4 1307.11   344.51306.656
     354 1305.26   362.7 1304.85   367.11306.701   368.7 1308.65   371.7 1313.44
   374.7 1316.37   376.2  1317.5   385.1 1321.79   389.5 1324.48   393.9  1328.7
   398.4 1331.56   407.2 1333.46   433.8 1335.04   442.7 1336.03   447.1 1336.88
   451.6  1339.2   460.4  1348.2   464.9 1349.79   495.9 1355.11   518.4 1358.07
#Mann= 7 ,-1 , 0
       0    .055       0    50.7     .06       0      88     .05       0
   344.5    .045       0   367.1     .05       0   451.6      .1       0
   518.4      .1       0
#XS Ineff= 2 , 0
          302.89 1314.18
Permanent Ineff=
       F       F
Bank Sta=344.5,367.1
XS Rating Curve= 0 ,0
Exp/Cntr=0.3,0.1

Type RM Length L Ch R = 1 ,6646    ,148.9,144.9,143.1
XS GIS Cut Line= 3
2465341.28136666668895.9137462862465469.36014865669127.102436296
2465825.22944919669156.614918323
#Sta/Elev= 30
       0 1314.81    94.9 1313.43   129.8 1313.66     171 1313.24   204.6 1311.55
   235.7 1310.96   264.3 1308.51   285.8 1307.27     350 1307.26     354 1306.92
     362 1304.86     366 1304.18     370 1303.92   382.1 1303.67   386.1 1304.22
   388.31305.057   406.2  1313.1   414.2 1317.32   426.2 1324.24   434.3 1327.24
   442.3 1329.12   474.4 1333.77   513.7 1334.09   534.6 1335.03   554.5 1336.54
   574.7 1337.03   586.8 1337.93   594.3 1339.14   607.4 1343.16   621.4 1345.95
#Mann= 4 ,-1 , 0
       0     .06       0   129.8     .05       0     362    .045       0
   388.3     .05       0
#XS Ineff= 2 , 0
           322.7 1311.51
Permanent Ineff=
       F       F
Bank Sta=362,388.3
XS Rating Curve= 0 ,0
Exp/Cntr(USF)=0,0
Exp/Cntr=0.3,0.1

Type RM Length L Ch R = 1 ,6501    ,239.8,243.1,246.4
XS GIS Cut Line= 3
2465333.56126942668913.2193583852465485.56685676669291.191886086
2465870.29685953669250.623441023
#Sta/Elev= 30
       0 1314.38   105.3 1312.89   149.8 1313.41   208.7 1311.28   292.6 1309.45
   355.8 1309.24   389.6 1308.09   428.7 1305.59   501.1 1305.02   505.1 1304.69
   507.9 1303.86   513.2 1302.59   529.2 1302.25   537.3 1302.54   543.81303.809
   553.4 1305.62   597.6 1307.59   608.9 1308.58   617.7 1310.93   629.8 1315.88
     638 1317.31   641.9 1318.85   649.9 1323.18   653.9 1324.54   694.2 1329.93
   762.5 1336.62   770.6 1338.58   782.6    1345   786.7 1346.52   794.3 1347.76
#Mann= 6 ,-1 , 0
       0     .06       0    47.1     .05       0   507.9    .045       0
   543.8     .05       0  643.98      .1       0  743.46    .055       0
Bank Sta=507.9,543.8
XS Rating Curve= 0 ,0
Exp/Cntr=0.3,0.1

Type RM Length L Ch R = 1 ,6258    ,298.3,290.7,276.6
XS GIS Cut Line= 3
2465461.28749612669283.9530930492465553.31508095669512.778439109
2465810.74359526669540.137991355
#Sta/Elev= 30
       0 1308.48    32.9 1307.35    46.9 1307.13      63 1307.14    80.3 1307.58
    97.5 1307.33   119.1 1307.35   178.4 1305.73   209.6 1305.16   253.2 1303.75
   269.3 1302.66   277.4 1302.39   289.4 1301.63   301.5 1301.47   305.31300.596
   309.5 1299.41   313.5 1298.98   317.6  1298.9     326 1299.75   337.7 1302.94
   341.7 1303.41   348.6 1303.71   359.5 1303.87   377.9 1303.69   385.9  1303.3
     398 1303.18   422.1 1303.51   426.2 1303.82   478.5 1303.51   505.5    1304
#Mann= 3 , 0 , 0
       0     .06       0   305.3    .045       0     326      .1       0
Bank Sta=305.3,326
XS Rating Curve= 0 ,0
Exp/Cntr(USF)=0,0
Exp/Cntr=0.3,0.1

Type RM Length L Ch R = 1 ,5967    ,76.3,75.3,75
XS GIS Cut Line= 3
 2465341.2859908669991.6717207352465830.11737399669686.923562691
2466031.18848763669616.375996874
#Sta/Elev= 30
       0 1348.18    48.9 1334.51    77.1 1328.69   181.6 1319.85   205.6    1314
   225.2 1314.62     260 1318.45   268.8  1318.1  278.791315.672   288.8 1311.95
   303.4 1304.73   311.5 1302.32   347.1 1302.71     353  1301.2     360 1297.44
   372.41296.426   379.1 1294.65   387.41297.213     393 1299.68   396.5 1300.05
   417.3 1298.77   452.7 1298.23   474.9 1299.66  494.151299.326   541.7 1300.93
   631.8 1300.52     697 1302.03   716.6 1303.82     746 1310.63   789.1 1316.65
#Mann= 5 ,-1 , 0
       0      .1       0  278.79     .06       0   372.4    .045       0
   387.4     .05       0  494.15    .055       0
#XS Ineff= 2 , 0
                          397.54         1304.18
Permanent Ineff=
       F       F
Bank Sta=372.4,387.4
XS Rating Curve= 0 ,0
Exp/Cntr=0.5,0.3

Type RM Length L Ch R = 1 ,5892    ,65.6,65.8,66
XS GIS Cut Line= 3
2465391.49511716670091.5689810822465885.09564406669715.951019151
2466051.23435799669643.716795703
#Sta/Elev= 30
       0 1355.61    37.1 1344.59    54.3 1340.81    89.5 1334.59   119.8 1326.53
   139.8 1324.48   154.9 1323.83   205.1 1324.39  253.341317.195   302.5 1309.64
   336.8 1302.87   345.9 1301.92   388.1  1301.5   393.9  1300.4   399.6 1297.15
     404 1294.76   408.1 1294.21   416.3 1295.46   421.3 1297.18   426.3 1299.32
   430.5 1299.72   445.2 1298.41  478.431298.012   516.6 1298.25   572.1 1299.96
   649.7 1299.25   710.5 1300.96   737.2 1304.14   783.4 1312.88   801.4 1315.29
#Mann= 5 ,-1 , 0
       0      .1       0  253.34     .06       0   399.6    .045       0
   421.3     .05       0  478.43    .055       0
#XS Ineff= 2 , 0
           393.5  1302.5  430.21          1301.7
Permanent Ineff=
       F       F
Bank Sta=399.6,421.3
XS Rating Curve= 0 ,0
Exp/Cntr(USF)=0,0
Exp/Cntr=0.5,0.3

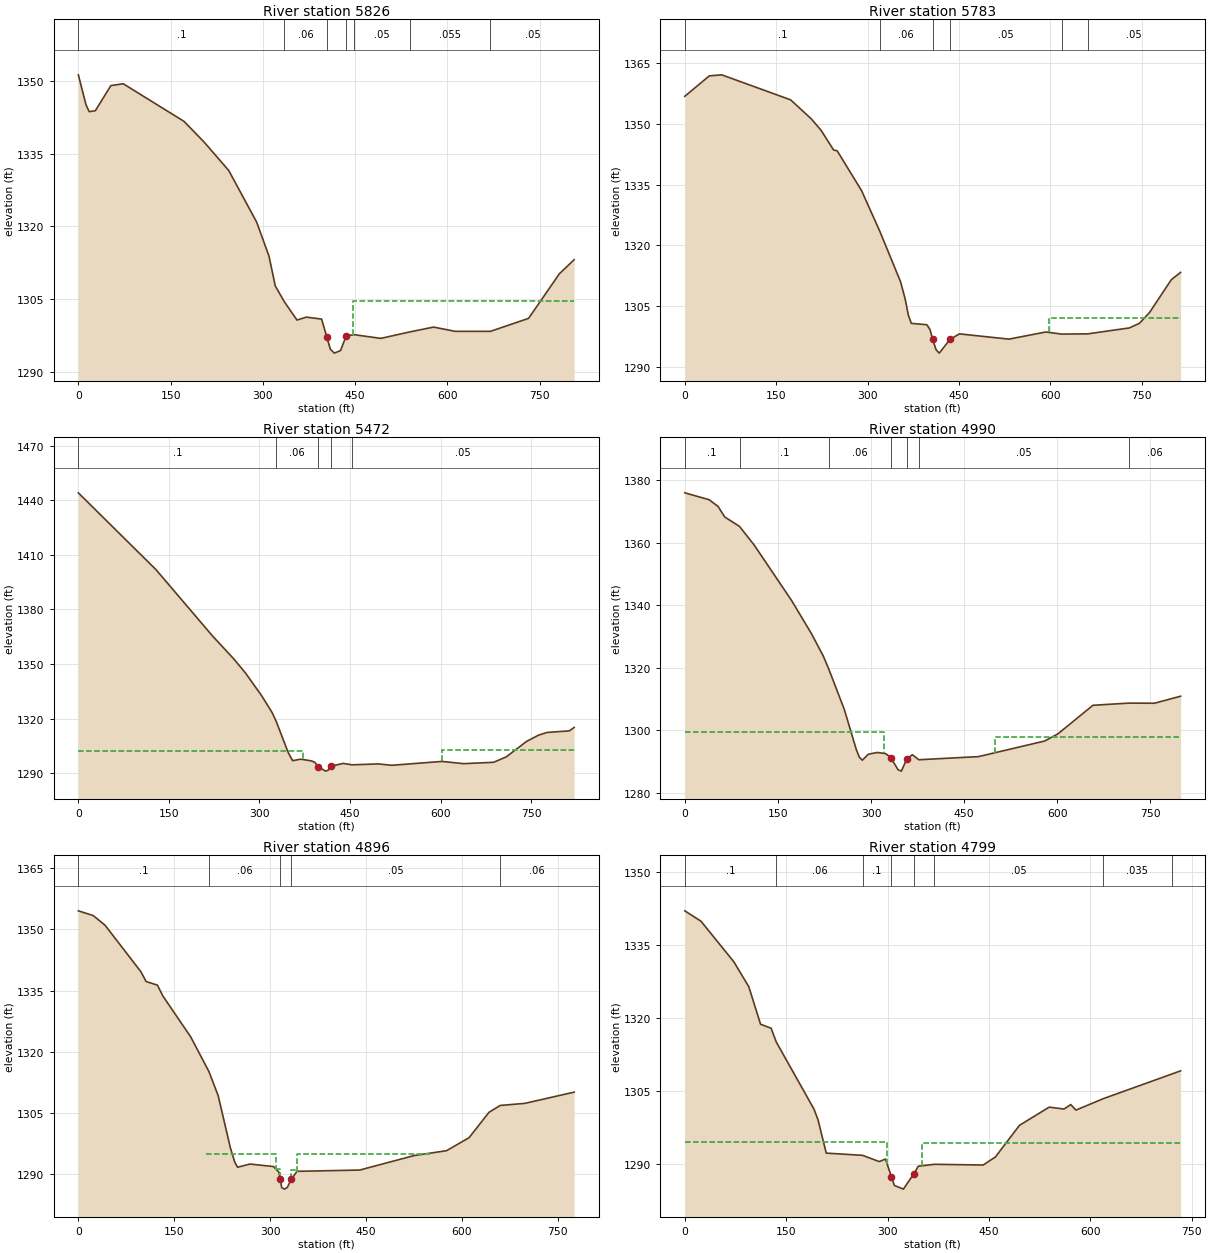
Type RM Length L Ch R = 1 ,5826    ,42.5,42.8,42.5
XS GIS Cut Line= 3
2465428.81973297670147.5261180692465935.65960047669758.087649496
2466092.96496276669702.543496828
#Sta/Elev= 30
       0 1351.27    12.5 1345.09    17.6 1343.68    27.7 1343.87    52.9 1349.05
      73 1349.43   171.7 1341.68   204.2 1337.44   244.6 1331.52     290 1320.86
   309.9 1313.89   320.2 1307.71  335.121304.424   355.5 1300.69   370.7  1301.3
   395.5 1300.89     404 1297.16   409.7 1294.68   416.1 1293.87   426.2  1294.4
   435.4 1297.39  447.951297.681   491.7 1296.91  538.781298.242   577.5 1299.24
   612.8 1298.36  669.971298.364   731.9 1301.04     782 1310.24     806 1313.14
#Mann= 7 ,-1 , 0
       0      .1       0  335.12     .06       0     404    .045       0
   435.4     .06       0  447.95     .05       0  538.78    .055       0
  669.97     .05       0
#XS Ineff= 2 , 0
                          445.78          1304.6
Permanent Ineff=
       F       F
Bank Sta=404,435.4
XS Rating Curve= 0 ,0
Exp/Cntr=0.5,0.3

Type RM Length L Ch R = 1 ,5783    ,313.2,311.2,307.9
XS GIS Cut Line= 3
2465451.23143012670190.6648844412465972.73983518669777.952060944
2466115.73952532669736.919347862
#Sta/Elev= 30
       0 1356.87    40.2 1361.92    60.6 1362.18   173.7 1355.99   207.4 1351.32
   223.8 1348.44   244.2 1343.59   250.1 1343.39   290.1 1333.55  320.331323.406
   354.2 1310.98   361.6 1306.81     367 1302.71   371.8 1300.71   397.3 1300.37
   402.4 1299.22   406.7 1296.82   412.4 1294.19   417.7 1293.35   435.2 1296.75
   450.8 1298.11     532 1296.81   592.6 1298.58  618.581298.054  661.481298.118
   729.6 1299.58   746.2 1300.72   762.9 1303.42   798.5 1311.51   813.8 1313.32
#Mann= 6 ,-1 , 0
       0      .1       0  320.33     .06       0   406.7    .045       0
   435.2     .05       0  618.58    .055       0  661.48     .05       0
#XS Ineff= 2 , 0
                           597.6            1302
Permanent Ineff=
       F       F
Bank Sta=406.7,435.2
XS Rating Curve= 0 ,0
Exp/Cntr=0.3,0.1

Type RM Length L Ch R = 1 ,5472    ,484.8,482.2,479.6
XS GIS Cut Line= 2
     2465714.736      670448.723     2466276.455      669849.464
#Sta/Elev= 30
       0 1444.02   128.6 1401.85     222 1365.54   257.4 1352.86   276.6 1345.22
   304.1  1332.4   321.1 1323.31  327.831318.487   347.9 1301.26     355 1296.91
   368.5 1297.76   386.2 1296.81   391.8 1296.01   397.7 1293.62   409.4 1291.19
   413.7 1291.67   419.2 1293.95   438.7 1295.43  453.251294.654   497.2 1295.15
   519.2 1294.39   602.5 1296.52     638 1295.29   687.8 1296.03   708.8 1298.98
   742.7 1307.54   762.5 1310.97   776.7 1312.43   813.5  1313.3   821.4 1315.19
#Mann= 5 ,-1 , 0
       0      .1       0  327.83     .06       0   397.7    .045       0
   419.2     .06       0  453.25     .05       0
#XS Ineff= 2 , 0
          372.58 1302.19  602.75         1303.03
Permanent Ineff=
       F       F
Bank Sta=397.7,419.2
XS Rating Curve= 0 ,0
Exp/Cntr=0.3,0.1

Type RM Length L Ch R = 1 ,4990    ,97.1,94.1,91.4
XS GIS Cut Line= 3
2466165.82573765670747.270859293 2466464.7842751670308.325822222
2466560.80467229 670058.40745977
#Sta/Elev= 30
       0 1375.89    39.2 1373.69    53.7 1371.51    64.3 1368.18   88.26 1365.13
   111.8 1359.19   172.2 1341.41   203.7 1330.97   223.1 1323.71  232.621319.188
     257 1306.61   276.3 1293.79   281.2 1291.34     286 1290.38   295.7  1292.3
   310.2 1292.85   323.4 1292.51   331.8 1291.24   343.5 1287.36   348.9 1286.89
   357.9  1290.9   366.6 1292.13  376.991290.528   473.1 1291.53   579.8 1296.52
   601.2 1298.82   657.5 1307.94  715.081308.639   756.6  1308.6   798.8 1310.85
#Mann= 7 ,-1 , 0
       0      .1       0   88.26      .1       0  232.62     .06       0
   331.8    .045       0   357.9     .06       0  376.99     .05       0
  715.08     .06       0
#XS Ineff= 2 , 0
          321.48 1299.52  499.44         1297.81
Permanent Ineff=
       F       F
Bank Sta=331.8,357.9
XS Rating Curve= 0 ,0
Exp/Cntr=0.5,0.3

Type RM Length L Ch R = 1 ,4896    ,95.7,96.7,98.6
XS GIS Cut Line= 2
2466314.97432371670813.4532392492466609.06254528670095.480661262
#Sta/Elev= 30
       0 1354.53    23.3 1353.37    41.7 1351.03    97.9 1339.62     106 1337.23
   123.8 1336.33   132.4 1333.65   175.7  1323.7  204.391315.163   218.9 1309.24
   237.9 1296.52   244.8 1293.01   249.2 1291.74   268.6 1292.52   305.4 1291.91
     314 1290.52     316 1288.74   318.3 1286.74   322.6 1286.38     327  1286.8
     333 1288.74   342.2 1290.74   440.3 1291.05   525.8 1294.61   576.2 1295.79
   611.5 1298.98   642.5 1305.17  660.041306.865   698.7 1307.38   775.9 1310.13
#Mann= 5 ,-1 , 0
       0      .1       0  204.39     .06       0     316    .045       0
     333     .05       0  660.04     .06       0
#XS Ineff= 4 ,-1
     200     310    1295     310     316  1291.3     333     342    1291
     342     550    1295
Permanent Ineff=
       F       F       F       F
Bank Sta=316,333
XS Rating Curve= 0 ,0
Exp/Cntr=0.5,0.3

Type RM Length L Ch R = 1 ,4799    ,84.9,84.7,84.1
XS GIS Cut Line= 2
2466394.99917919670836.7163170142466701.68478748 670170.16849553
#Sta/Elev= 30
       0 1342.04      24  1339.9    72.5 1331.57    94.7 1326.43   112.1 1318.71
   127.8 1317.88  135.251315.076   191.2 1301.24   197.2 1299.02   209.3 1292.19
  263.011291.733   287.7 1290.45     297 1290.96   305.8  1287.3   305.8 1287.26
   310.2 1285.54   323.4 1284.78   338.6 1287.87   345.5 1289.49  369.281289.889
   441.5 1289.74   459.6 1291.39   495.2  1297.9   539.2 1301.65   561.2 1301.26
   571.1 1302.18   578.8 1301.04  618.991303.378  720.331308.444   733.7 1309.12
#Mann= 8 ,-1 , 0
       0      .1       0  135.25     .06       0  263.01      .1       0
   305.8    .045       0   338.6      .1       0  369.28     .05       0
  618.99    .035       0  720.33    .055       0
#XS Ineff= 2 , 0
          299.91 1294.54  350.59         1294.25
Permanent Ineff=
       F       F
Bank Sta=305.8,338.6
XS Rating Curve= 0 ,0
Exp/Cntr=0.5,0.3

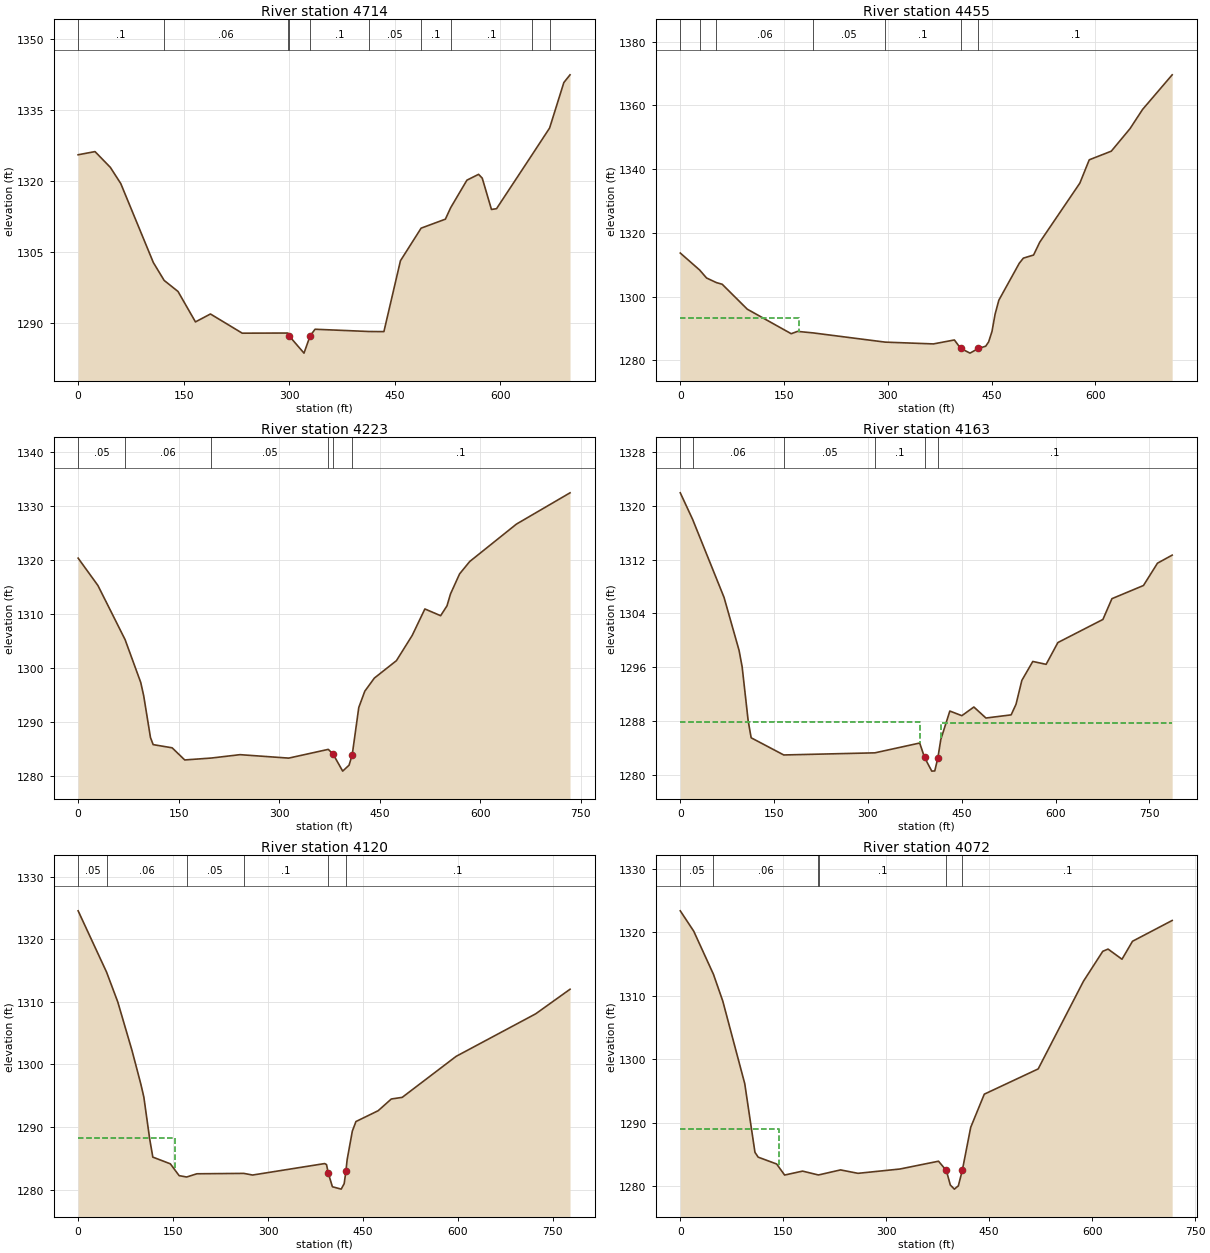
Type RM Length L Ch R = 1 ,4714    ,257.5,259.1,260
XS GIS Cut Line= 2
2466480.84138286670864.8391467292466762.29124691670224.668881936
#Sta/Elev= 30
       0 1325.53      24  1326.2    45.8 1322.87    60.6 1319.46     107 1302.76
  122.331299.009     142 1296.68   166.8 1290.26   188.1 1291.93   233.3 1287.88
  298.09 1287.91   300.4 1287.23   321.1 1283.67   329.8 1287.31   336.8 1288.71
  413.821288.231   434.7 1288.21   458.2 1303.16   487.61310.042   522.1 1311.94
  529.551314.343   552.7 1320.17   569.3  1321.4   574.5  1320.6   587.6 1313.99
   594.8 1314.15  645.281325.517  670.241331.168   690.5 1340.77   699.3  1342.4
#Mann= 10 ,-1 , 0
       0      .1       0  122.33     .06       0  298.09      .1       0
   300.4    .045       0   329.8      .1       0  413.82     .05       0
   487.6      .1       0  529.55      .1       0  645.28    .035       0
  670.24      .1       0
Bank Sta=300.4,329.8
XS Rating Curve= 0 ,0
Exp/Cntr=0.3,0.1

Type RM Length L Ch R = 1 ,4455    ,230,232,232.5
XS GIS Cut Line= 2
     2466656.823      671020.3272466992.17486692670393.151664368
#Sta/Elev= 30
       0 1313.69   28.031308.359      38 1305.86   52.231304.418    60.6  1303.9
    96.9 1296.07   160.4 1288.38   169.5 1289.11  191.761288.642  296.381285.739
     366 1285.18   396.3 1286.42   405.3  1283.8   418.9 1282.29     431 1283.76
   441.6 1284.46   445.8  1285.8   450.7 1289.11   455.2 1294.54   460.6  1298.9
   490.1 1310.47   496.1  1312.1   510.8 1313.06   519.7 1317.08   577.7 1335.62
   591.3 1342.94   623.2 1345.65   650.3 1352.73   668.4 1358.74   711.2  1369.6
#Mann= 7 ,-1 , 0
       0     .05       0   28.03      .1       0   52.23     .06       0
  191.76     .05       0  296.38      .1       0   405.3    .045       0
     431      .1       0
#XS Ineff= 2 , 0
          171.23 1293.44
Permanent Ineff=
       F       F
Bank Sta=405.3,431
XS Rating Curve= 0 ,0
Exp/Cntr=0.3,0.1

Type RM Length L Ch R = 1 ,4223    ,59.8,60.3,60.5
XS GIS Cut Line= 2
2466841.08999875 671101.865722542467229.01453209670479.105647954
#Sta/Elev= 30
       0 1320.29    29.5 1315.23   70.031305.201    93.4 1297.26    97.8  1294.8
   107.9 1287.06   111.9 1285.75   140.2 1285.16     159 1282.91  198.771283.265
   241.5 1283.89   314.1 1283.25  373.131284.871   380.5 1283.95   394.6 1280.84
   404.1 1281.94   408.8 1283.83   418.6 1292.63   427.6 1295.65   441.8 1298.07
   474.8 1301.31   498.3 1305.98   517.2 1310.88   540.7 1309.63   550.2 1311.46
   555.4 1313.66     569 1317.38   584.1 1319.67   653.8  1326.6   733.7 1332.39
#Mann= 6 ,-1 , 0
       0     .05       0   70.03     .06       0  198.77     .05       0
  373.13      .1       0   380.5    .045       0   408.8      .1       0
Bank Sta=380.5,408.8
XS Rating Curve= 0 ,0
Exp/Cntr(USF)=0,0
Exp/Cntr=0.5,0.3

Type RM Length L Ch R = 1 ,4163    ,43.5,42.5,42.1
XS GIS Cut Line= 2
2466879.30091264671129.0758500642467316.28894738670475.349442912
#Sta/Elev= 30
       0 1321.94    19.71317.997      70 1306.37      94 1298.49    98.9 1296.04
   108.5 1288.04   113.3 1285.49   165.41282.935  311.111283.251   382.7 1284.71
   390.5 1282.56     402 1280.53   406.8 1280.56   411.81282.515   416.4 1285.22
   430.9 1289.47   450.1 1288.78   469.3 1290.07   488.6 1288.43   528.9  1288.9
   536.7 1290.48     546 1294.03   563.5 1296.85   584.8 1296.42   603.6 1299.66
   675.6  1303.1     690 1306.19   740.4 1308.15   762.8 1311.47   786.3 1312.67
#Mann= 6 ,-1 , 0
       0     .05       0    19.7     .06       0   165.4     .05       0
  311.11      .1       0   390.5    .045       0   411.8      .1       0
#XS Ineff= 2 , 0
          382.79 1287.84   417.2          1287.7
Permanent Ineff=
       F       F
Bank Sta=390.5,411.8
XS Rating Curve= 0 ,0
Exp/Cntr=0.5,0.3

Type RM Length L Ch R = 1 ,4120    ,48,48.3,48.5
XS GIS Cut Line= 2
2466930.13912516 671168.074558112467327.61709732670500.273318774
#Sta/Elev= 30
       0 1324.52    44.91314.739    62.6 1309.98    85.2 1302.19    99.1 1296.84
   103.8 1294.79   113.1 1288.06     118  1285.2   145.7 1284.13   159.6 1282.24
  171.471282.027   187.6 1282.54   261.71282.602   275.6 1282.34   389.4 1284.17
   392.4 1284.01   395.2 1282.63   401.7 1280.47   415.6 1280.09   420.3 1280.97
     4231282.921     425  1284.8   433.2 1289.36   438.9 1290.88     474 1292.61
   494.8 1294.48     512 1294.74   597.2 1301.29   722.9 1308.08   777.1    1312
#Mann= 6 ,-1 , 0
       0     .05       0    44.9     .06       0  171.47     .05       0
   261.7      .1       0   395.2    .045       0     423      .1       0
#XS Ineff= 2 , 0
          153.76 1288.24
Permanent Ineff=
       F       F
Bank Sta=395.2,423
XS Rating Curve= 0 ,0
Exp/Cntr=0.5,0.3

Type RM Length L Ch R = 1 ,4072    ,601.3,607.6,600.3
XS GIS Cut Line= 2
2466970.39817653 671183.612271712467344.94600182670572.742604276
#Sta/Elev= 30
       0  1323.4    19.6 1320.19   48.35 1313.39    61.9 1309.18    93.9 1296.17
   108.8 1285.33   113.5 1284.57   140.4 1283.49     152 1281.75   178.2 1282.37
  200.581281.778  201.62 1281.77   233.5 1282.56   258.9 1282.02   319.9  1282.7
   376.2 1283.93   387.6 1282.47   393.4 1280.18   399.3 1279.53   405.1 1280.05
   410.9  1282.5   423.1 1289.27   442.9  1294.5   521.4 1298.48   587.3 1312.29
   615.5 1317.02   623.2 1317.37   643.5 1315.77   658.8  1318.6   716.6 1321.88
#Mann= 6 ,-1 , 0
       0     .05       0   48.35     .06       0  200.58     .05       0
  201.62      .1       0   387.6    .045       0   410.9      .1       0
#XS Ineff= 2 , 0
          143.67 1289.05
Permanent Ineff=
       F       F
Bank Sta=387.6,410.9
XS Rating Curve= 0 ,0
Exp/Cntr(USF)=0,0
Exp/Cntr=0.3,0.1

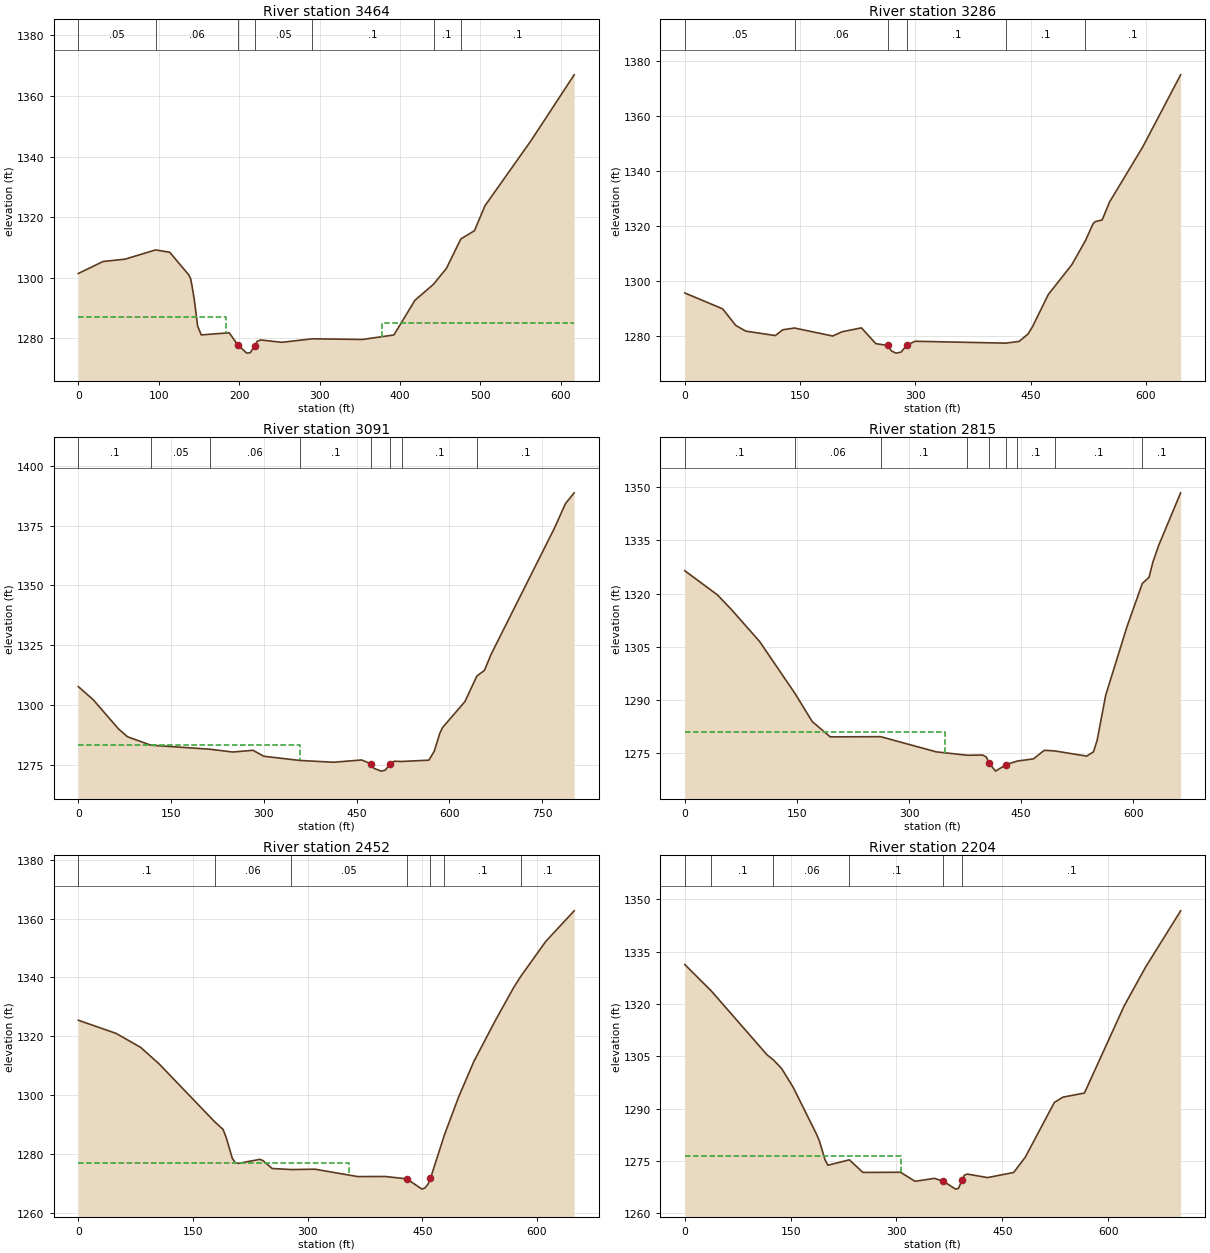
Type RM Length L Ch R = 1 ,3464    ,176.2,178.7,181.2
XS GIS Cut Line= 2
 2467274.7568143 671359.171883782467518.87613547670793.083817807
#Sta/Elev= 30
       0 1301.42    30.8 1305.38      58 1306.14   95.971309.194   113.6 1308.44
   137.2    1301   139.7 1299.64   141.4 1297.26   144.1 1292.94   148.4 1284.03
   152.8 1281.14   187.6 1281.83     198 1277.95   209.4 1275.12   213.8 1275.26
   219.3 1277.52   222.5 1279.04   226.8 1279.46     253 1278.69  290.921279.848
   353.3 1279.63   392.4 1281.12   418.5 1292.56  441.611297.858   457.7 1303.11
  475.571312.815   492.5 1315.53   505.6 1323.78   563.3 1345.44   616.5 1367.01
#Mann= 7 ,-1 , 0
       0     .05       0   95.97     .06       0     198    .045       0
   219.3     .05       0  290.92      .1       0  441.61      .1       0
  475.57      .1       0
#XS Ineff= 2 , 0
          183.34 1287.19  378.05          1285.1
Permanent Ineff=
       F       F
Bank Sta=198,219.3
XS Rating Curve= 0 ,0
Exp/Cntr=0.3,0.1

Type RM Length L Ch R = 1 ,3286    ,190.6,194.2,192.7
XS GIS Cut Line= 3
2467292.89642592671365.9138058662467484.62924124671291.598761165
2467712.03327803670915.564634981
#Sta/Elev= 30
       0 1295.68    49.2 1289.91    66.3 1283.88    79.2  1281.8   117.8 1280.18
   127.4 1282.28  142.751282.927   192.4 1280.02   204.7 1281.57   229.8 1282.99
   248.5 1277.25   263.8 1276.59   268.9 1274.58   274.7 1273.79   281.3 1274.15
   289.3  1276.8   299.9 1278.11  417.311277.426   434.9 1278.04   446.6 1280.76
   452.4 1283.41   472.9 1295.11   503.5 1305.95  521.19 1314.69     531 1320.78
   533.9 1321.64     543 1322.26   552.4 1328.66   596.2 1349.03   645.1 1375.07
#Mann= 6 ,-1 , 0
       0     .05       0  142.75     .06       0   263.8    .045       0
   289.3      .1       0  417.31      .1       0  521.19      .1       0
Bank Sta=263.8,289.3
XS Rating Curve= 0 ,0
Exp/Cntr(USF)=0,0
Exp/Cntr=0.3,0.1

Type RM Length L Ch R = 1 ,3091    ,262.2,276.7,282.5
XS GIS Cut Line= 3
2467400.14249553671622.467097318 2467591.5577596671435.757959177
2467839.20897318670962.408442912
#Sta/Elev= 30
       0 1307.67    24.2 1302.14    65.1 1289.91    79.6 1286.66  117.311283.133
   212.81281.449   249.5 1280.28   282.3    1281     300  1278.5  358.541276.741
   412.7    1276     458 1276.95   472.7 1275.39   477.9 1273.44   489.6 1272.28
   495.71272.629   504.5 1275.16   510.5 1276.42  522.921276.322   566.8 1276.87
   575.4 1280.61   584.4 1288.12   588.9 1290.54     625 1301.39  644.171312.028
   656.6 1314.48   667.5 1321.28   769.5 1373.87   787.5 1384.25   801.6 1388.78
#Mann= 8 ,-1 , 0
       0      .1       0  117.31     .05       0   212.8     .06       0
  358.54      .1       0   472.7    .045       0   504.5      .1       0
  522.92      .1       0  644.17      .1       0
#XS Ineff= 2 , 0
          358.11  1283.2
Permanent Ineff=
       F       F
Bank Sta=472.7,504.5
XS Rating Curve= 0 ,0
Exp/Cntr=0.3,0.1

Type RM Length L Ch R = 1 ,2815    ,346,362.5,373
XS GIS Cut Line= 3
     2467449.022      671667.7652467612.09635448 671555.17708046
2467962.67464644671249.420627127
#Sta/Elev= 30
       0 1326.41    43.8 1319.59    62.3 1315.51   100.1 1306.49  147.411291.869
   170.5 1283.96   194.5 1279.66  262.021279.706   336.3 1275.44   378.11274.475
   398.7 1274.53   403.4 1273.96   407.2 1272.25   415.7 1270.01   429.9 1271.84
   429.9 1271.85  444.731272.839   466.4 1273.46   480.9 1275.87  495.061275.694
   537.6 1274.23   546.7 1275.44   551.6 1278.68   563.1  1291.4   591.5 1310.64
  612.031322.816     621 1324.56   626.3 1328.91     634 1333.57   663.3 1348.34
#Mann= 9 ,-1 , 0
       0      .1       0  147.41     .06       0  262.02      .1       0
   378.1     .05       0   407.2    .045       0   429.9     .05       0
  444.73      .1       0  495.06      .1       0  612.03      .1       0
#XS Ineff= 2 , 0
          348.23 1280.91
Permanent Ineff=
       F       F
Bank Sta=407.2,429.9
XS Rating Curve= 0 ,0
Exp/Cntr=0.3,0.1

Type RM Length L Ch R = 1 ,2452    ,240.9,248.4,251
XS GIS Cut Line= 2
2467505.42442851671669.9351305752468153.76339172671647.463341609
#Sta/Elev= 30
       0 1325.48    49.4 1321.01    81.4 1316.29   105.4 1310.73  178.551290.964
   189.4 1288.39   193.4 1285.71   201.4 1278.65   205.4 1277.06   209.4 1276.88
   237.5 1278.24   241.5 1277.82   253.5 1275.14  278.661274.777   309.5  1274.9
   365.5 1272.39   401.6 1272.42   429.7 1271.62   449.6 1268.13   453.6 1268.56
   457.6 1269.85   460.7 1271.76  478.88 1286.49   497.6 1299.46   517.6 1311.55
   545.6  1325.4   569.7 1336.64  578.99 1340.42   611.5 1352.23   648.7 1362.63
#Mann= 7 ,-1 , 0
       0      .1       0  178.55     .06       0  278.66     .05       0
   429.7    .045       0   460.7     .05       0  478.88      .1       0
  578.99      .1       0
#XS Ineff= 2 , 0
          353.89 1277.15
Permanent Ineff=
       F       F
Bank Sta=429.7,460.7
XS Rating Curve= 0 ,0
Exp/Cntr=0.3,0.1

Type RM Length L Ch R = 1 ,2204    ,374.4,371.6,353.2
XS GIS Cut Line= 2
 2467589.3676892671805.8906335632468272.88413057671968.866497011
#Sta/Elev= 30
       0 1331.32   37.711323.708   116.6 1305.42   125.71303.946   137.1 1301.53
   153.6 1296.12   186.5 1282.74   190.6 1280.82   198.8  1275.3   202.9 1273.77
  233.291275.316   252.3  1271.7   305.7 1271.75   326.3 1269.16   353.9    1270
   366.5 1269.15   383.8 1266.91     388 1267.16   392.71269.389   396.2 1270.89
   400.3 1271.23   429.1 1270.22   466.1 1271.69   482.5 1276.06   523.7 1291.76
     536 1293.29   566.4 1294.47   622.3  1319.3   652.8  1330.5   702.7 1346.72
#Mann= 6 ,-1 , 0
       0      .1       0   37.71      .1       0   125.7     .06       0
  233.29      .1       0   366.5    .045       0   392.7      .1       0
#XS Ineff= 2 , 0
          306.56 1276.27
Permanent Ineff=
       F       F
Bank Sta=366.5,392.7
XS Rating Curve= 0 ,0
Exp/Cntr=0.3,0.1

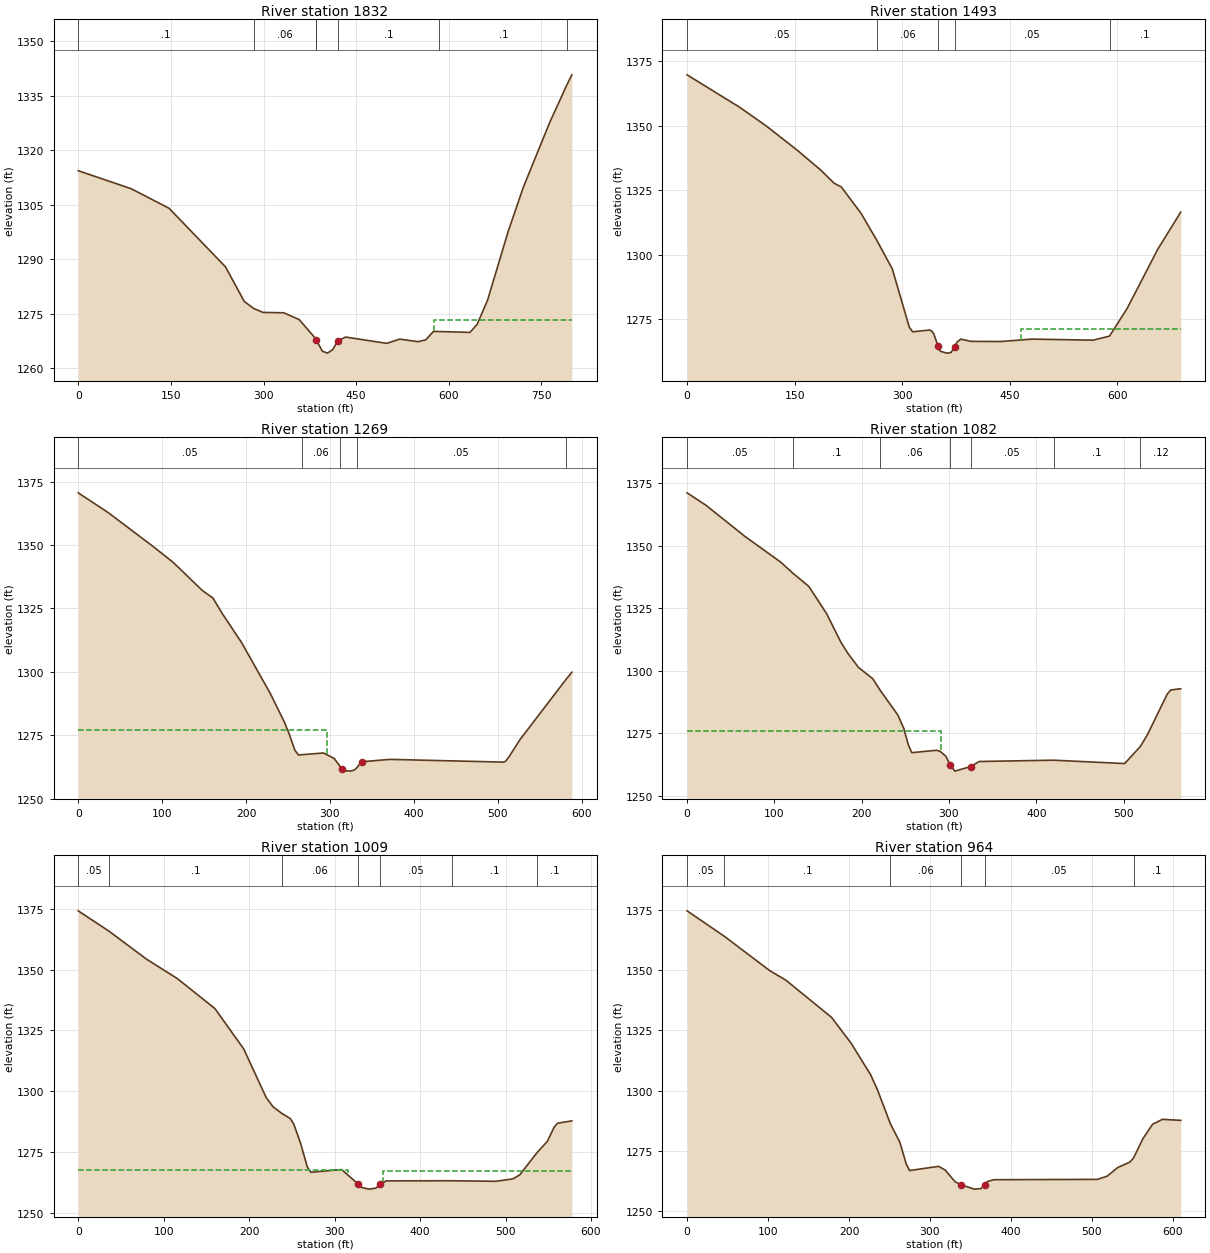
Type RM Length L Ch R = 1 ,1832    ,341.9,339.2,332.5
XS GIS Cut Line= 2
2467492.59128611672244.3074305622468257.30724652672011.625852763
#Sta/Elev= 30
       0 1314.36    86.2 1309.37   147.1 1304.02   238.5 1287.91   268.9 1278.39
  284.291276.458   299.1 1275.39   332.6 1275.28   357.6 1273.44  384.511268.172
   385.7 1267.73   395.3 1264.72   403.6 1264.19     412 1265.15   420.4 1267.55
   432.9 1268.61   499.5 1266.88   520.7 1268.04     550 1267.34   562.5 1267.82
   575.1 1270.14  584.961270.127   634.4 1269.89   646.1 1272.16   662.9  1278.8
   696.3 1297.72   720.9 1309.89   763.2 1327.53  791.661338.123   799.3 1340.72
#Mann= 7 ,-1 , 0
       0      .1       0  284.29     .06       0  384.51      .1       0
   385.7    .045       0   420.4      .1       0  584.96      .1       0
  791.66      .1       0
#XS Ineff= 2 , 0
                          576.07         1273.21
Permanent Ineff=
       F       F
Bank Sta=385.7,420.4
XS Rating Curve= 0 ,0
Exp/Cntr=0.3,0.1

Type RM Length L Ch R = 1 ,1493    ,219.8,223.6,227.1
XS GIS Cut Line= 2
     2467693.575672620.879450483 2468273.8064377672250.370420112
#Sta/Elev= 30
       0 1369.77    72.6 1357.32   109.5 1350.13   153.3 1340.61   186.5  1332.8
     205 1327.75     215 1326.31   242.7 1316.02  264.571305.608   286.2 1294.49
   309.9 1271.91   314.6  1270.1   338.2 1270.81   341.2 1270.39   344.1 1269.29
   349.9 1264.62     353 1262.59   362.1 1261.84   367.9 1262.05     373 1264.09
   376.3 1266.05   381.7 1267.28   396.2 1266.39     438 1266.35   480.7 1267.28
   566.2 1266.86   589.11268.439   613.6 1279.14   656.3 1302.09   688.4 1316.53
#Mann= 5 ,-1 , 0
       0     .05       0  264.57     .06       0   349.9    .045       0
     373     .05       0   589.1      .1       0
#XS Ineff= 2 , 0
                          465.55         1271.24
Permanent Ineff=
       F       F
Bank Sta=349.9,373
XS Rating Curve= 0 ,0
Exp/Cntr=0.3,0.1

Type RM Length L Ch R = 1 ,1269    ,184.7,187.4,190.3
XS GIS Cut Line= 2
2467803.88450796672729.3861380072468357.11367618672528.940787204
#Sta/Elev= 30
       0 1370.58    35.4 1362.87    88.1 1349.73   113.7 1343.02   147.8 1332.11
   160.5 1329.13   171.7 1322.99   194.7 1311.57     229 1291.44   245.5 1280.35
   250.9 1276.02   258.3 1269.06   262.6 1267.22   266.8 1267.36   292.3 1268.02
   305.1 1265.87   312.6 1262.53   314.81261.746   317.9 1261.06   324.4 1260.87
     329 1261.27   332.1 1262.22   337.8 1264.56   371.3  1265.5     507 1264.42
   509.3 1264.73   513.6 1266.57   526.3 1273.19   581.1 1296.88   588.4 1299.86
#Mann= 5 ,-1 , 0
       0     .05       0   266.8     .06       0   312.6    .045       0
   332.1     .05       0   581.1      .1       0
#XS Ineff= 2 , 0
          296.84 1277.11
Permanent Ineff=
       F       F
Bank Sta=314.8,337.8
XS Rating Curve= 0 ,0
Exp/Cntr(USF)=0,0
Exp/Cntr=0.3,0.1

Type RM Length L Ch R = 1 ,1082    ,69.7,73,73.7
XS GIS Cut Line= 2
2467853.41304902672849.9975054742468409.97305348672749.861532294
#Sta/Elev= 30
       0 1371.23    21.7 1366.23    66.4 1353.77     107 1343.57  121.811338.891
   139.5 1333.78   159.9 1322.85     176  1311.6   184.2    1307   196.4 1301.34
   212.7 1296.85  221.141292.256   241.5 1282.29   248.4 1276.83   253.3 1270.55
   257.4 1267.26   285.8 1268.21   289.9  1267.8   296.6 1265.77   301.21262.289
   306.9 1259.87   324.9  1261.7   334.6 1263.72   419.81264.244   501.3  1262.9
  519.131269.687   527.4 1274.46     550 1290.67   554.1 1292.34   565.5 1292.83
#Mann= 7 ,-1 , 0
       0     .05       0  121.81      .1       0  221.14     .06       0
   301.2    .045       0   324.9     .05       0   419.8      .1       0
  519.13     .12       0
#XS Ineff= 2 , 0
          291.15 1275.97
Permanent Ineff=
       F       F
Bank Sta=301.2,324.9
XS Rating Curve= 0 ,0
Exp/Cntr=0.5,0.3

Type RM Length L Ch R = 1 ,1009    ,44.2,44.9,45.4
XS GIS Cut Line= 3
2467842.83660036672867.3953363772468034.13690213672872.608239503
2468419.50648423672846.928973067
#Sta/Elev= 30
       0 1374.08   36.341365.658    79.9 1354.26     116 1346.28     160 1333.97
   193.6 1317.45     220 1297.45   228.1 1293.66  237.911291.079   248.1 1288.88
   252.1 1286.68   260.1 1278.84   268.1    1269   272.2 1266.85   308.2 1267.97
   327.6 1261.99   332.3 1260.57   340.3 1259.93   348.3 1260.34   353.4 1261.88
   360.4 1263.32  437.421263.364   488.6 1263.14   508.7 1264.14   516.7 1265.81
  537.181275.052   548.8 1279.47   556.8 1285.29   560.8 1286.96   577.6 1287.93
#Mann= 7 ,-1 , 0
       0     .05       0   36.34      .1       0  237.91     .06       0
   327.6    .045       0   353.4     .05       0  437.42      .1       0
  537.18      .1       0
#XS Ineff= 2 , 0
          315.87  1267.8   356.6          1267.4
Permanent Ineff=
       F       F
Bank Sta=327.6,353.4
XS Rating Curve= 0 ,0
Exp/Cntr(USF)=0,0
Exp/Cntr=0.5,0.3

Type RM Length L Ch R = 1 ,964     ,60,66.1,71.7
XS GIS Cut Line= 3
2467837.41097186672887.8060372412468053.51975209672911.939774171
2468445.50374565672896.742080827
#Sta/Elev= 30
       0 1374.71   46.011364.131     102 1349.87   122.1 1345.87   178.4 1330.44
   202.6 1319.68   226.7 1306.58   235.1 1300.37  251.191286.135   262.7 1278.59
   270.7 1269.49   274.7 1266.76   310.7 1268.51   318.8 1266.96   330.8 1262.18
   338.4 1260.81   354.8 1259.04   362.8 1259.25   367.6 1260.79   370.8 1262.17
   378.8 1262.96   506.9 1263.09   518.9 1264.45   531.8 1267.99   546.9 1270.28
  551.371271.948   562.9 1279.95   574.9 1285.98     587 1288.04   609.7 1287.63
#Mann= 6 ,-1 , 0
       0     .05       0   46.01      .1       0  251.19     .06       0
   338.4    .045       0   367.6     .05       0  551.37      .1       0
Bank Sta=338.4,367.6
XS Rating Curve= 0 ,0
Exp/Cntr=0.5,0.3