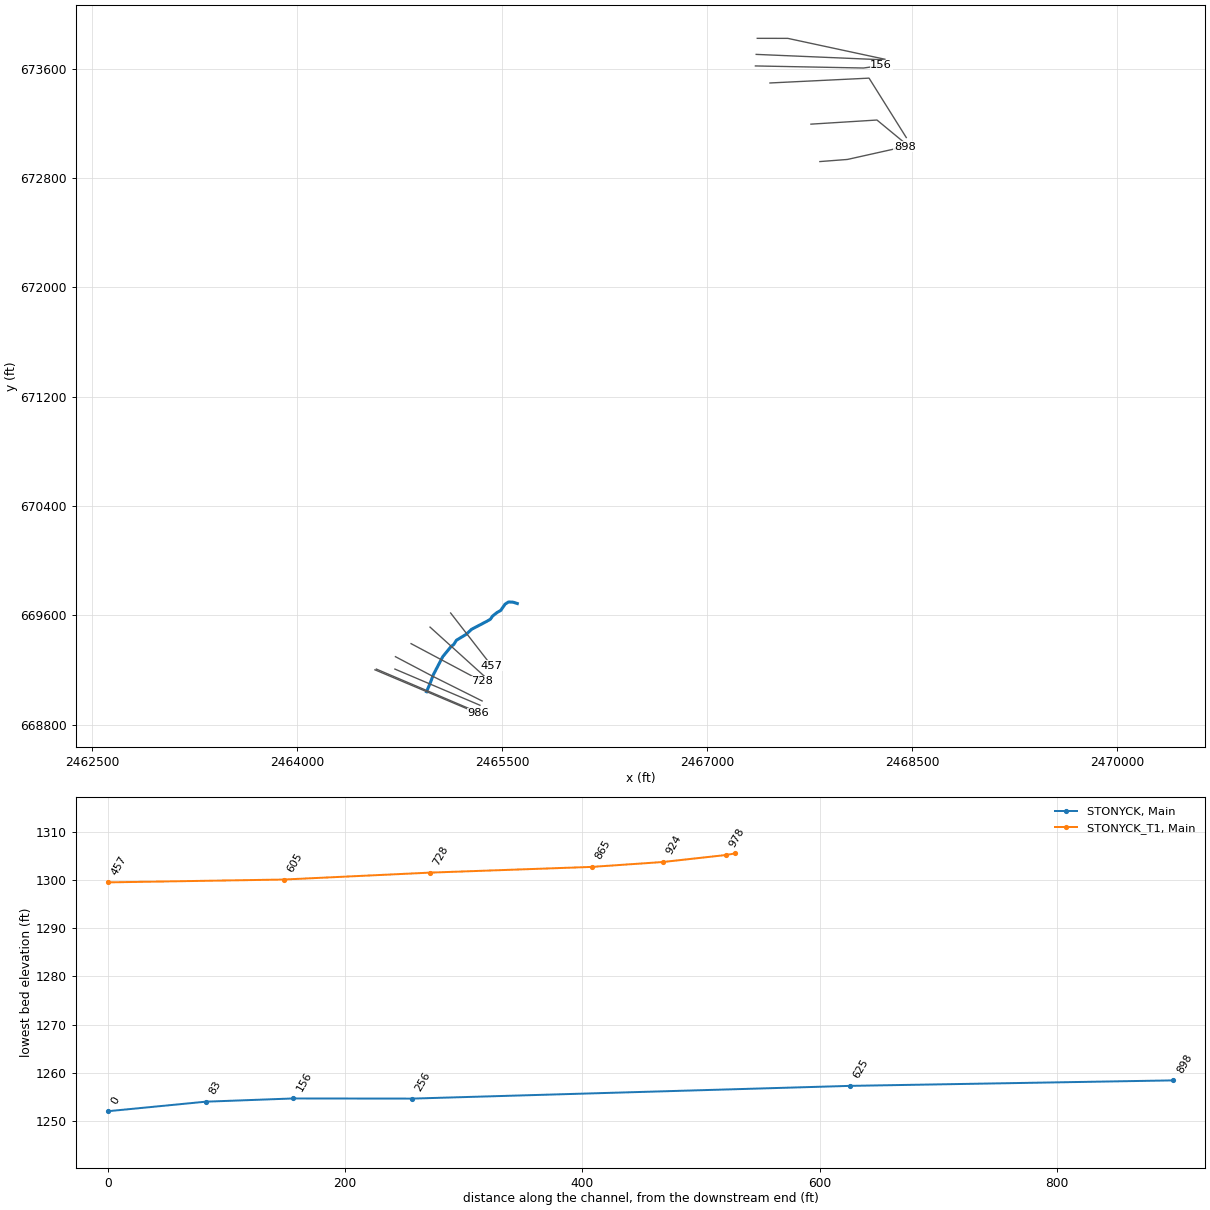
HEC-RAS study STONYCK_T1.prj: STONYCK_T1

--- STONYCK_T1.g01 (geometry) --- (continued)

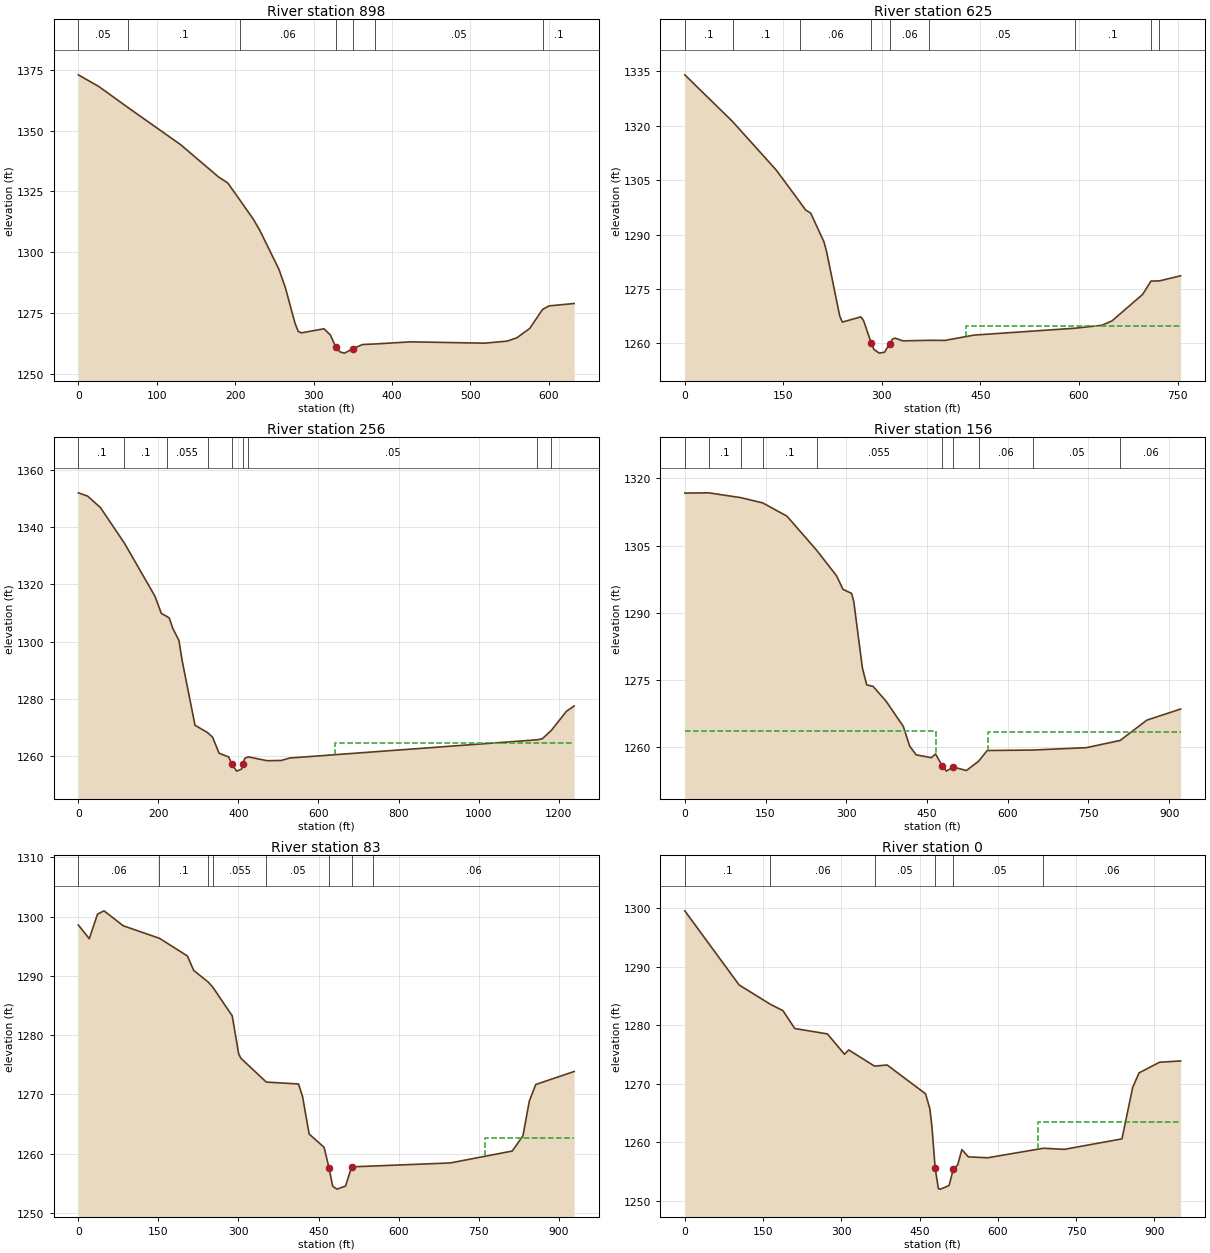
Type RM Length L Ch R = 1 ,898     ,274.6,272.6,267.6
XS GIS Cut Line= 3
2467824.82214925 672919.870506342468026.29849266672935.394093455
2468446.09592294673029.031049778
#Sta/Elev= 30
       0 1373.03      26 1368.25   63.671359.481   130.3 1344.31   178.5 1331.05
   190.5 1328.51  206.351321.315     223 1313.63   231.2 1309.11   255.8 1292.93
     264 1285.38   276.3 1270.71   280.4 1267.35   284.5 1266.78   313.2 1268.46
   321.4 1265.87   328.4 1260.85   333.7 1258.92   339.4 1258.43   350.1 1260.26
   362.4 1261.98  378.07  1262.2   423.8 1263.08   518.1 1262.53   546.8 1263.38
   559.1 1264.74   575.5 1268.59  591.97 1276.45   600.1 1277.88632.1871 1278.87
#Mann= 7 ,-1 , 0
       0     .05       0   63.67      .1       0  206.35     .06       0
   328.4    .045       0   350.1     .06       0  378.07     .05       0
  591.97      .1       0
Bank Sta=328.4,350.1
XS Rating Curve= 0 ,0
Exp/Cntr(USF)=0,0
Exp/Cntr=0.3,0.1

Type RM Length L Ch R = 1 ,625     ,367.9,369.2,367.4
XS GIS Cut Line= 3
2467759.38969979673193.7358189092468242.37292766673223.867335737
2468451.34533822673051.711511259
#Sta/Elev= 30
       0 1334.06   72.781321.164   139.1 1307.81  174.621299.103   183.7 1296.82
   191.7 1295.89   211.8 1287.99   215.8 1285.33   235.8 1267.55   239.8 1265.85
   267.9 1267.29   272.1 1266.27   283.9 1260.02   287.9 1258.31   295.9 1257.29
   303.9 1257.53     312 1259.94     316 1261.13     320 1261.43     332 1260.67
  371.941260.831   396.1  1260.8   440.2 1262.26  594.641264.173   634.7 1264.97
   650.2 1266.18   696.9 1273.49  709.641277.167  722.381277.216   754.7 1278.63
#Mann= 9 ,-1 , 0
       0      .1       0   72.78      .1       0  174.62     .06       0
   283.9    .045       0     312     .06       0  371.94     .05       0
  594.64      .1       0  709.64     .05       0  722.38      .1       0
#XS Ineff= 2 , 0
                          427.89         1264.82
Permanent Ineff=
       F       F
Bank Sta=283.9,312
XS Rating Curve= 0 ,0
Exp/Cntr(USF)=0,0
Exp/Cntr=0.3,0.1

Type RM Length L Ch R = 1 ,256     ,99.4,99.9,98.5
XS GIS Cut Line= 3
2467459.60464441673495.0552505962468184.67264513673530.424964094
2468456.94662065 673095.72573837
#Sta/Elev= 30
       0 1352.08    23.2 1350.94    55.2 1346.92  115.151334.472   191.4  1315.9
   207.4 1309.86  221.331308.795   227.4 1308.21   235.4 1304.83   251.4 1300.39
   259.4 1293.37   291.5 1270.73  322.861268.147   335.5 1266.53   351.6 1260.93
   375.6 1259.62   383.6 1257.12   395.6 1254.65   407.7 1255.33   411.6 1257.29
   415.6 1259.08   424.4 1259.65   471.7  1258.3   506.9 1258.38   527.8 1259.23
 1146.721265.616  1159.4 1265.99 1182.181268.963  1219.6 1275.59  1238.9 1277.47
#Mann= 9 ,-1 , 0
       0      .1       0  115.15      .1       0  221.33    .055       0
  322.86     .06       0   383.6    .045       0   411.6     .06       0
   424.4     .05       0 1146.72      .1       0 1182.18     .05       0
#XS Ineff= 2 , 0
                          642.39         1264.56
Permanent Ineff=
       F       F
Bank Sta=383.6,411.6
XS Rating Curve= 0 ,0
Exp/Cntr(USF)=0,0
Exp/Cntr=0.5,0.3

Type RM Length L Ch R = 1 ,156     ,74.1,73.8,74.9
XS GIS Cut Line= 3
2467352.83195207673619.6781632562468144.88021219673604.508976331
2468272.73478769673622.928703311
#Sta/Elev= 30
       0 1316.71   44.331316.771  103.881315.702  144.651314.532   189.9 1311.56
  244.971303.967     282 1298.26     294 1295.23     310 1294.33     314 1292.51
     330 1277.73     338 1273.93     350 1273.58     374 1270.29     406 1264.67
     418 1260.24     430 1258.31     458 1257.69   466.1  1258.5   478.4 1255.83
     486 1254.68   498.8  1255.6   523.2 1254.81  545.921256.886     562 1259.28
  646.241259.384     746 1259.91  809.081261.528   858.7 1266.06921.3681 1268.53
#Mann= 10 ,-1 , 0
       0      .1       0   44.33      .1       0  103.88     .06       0
  144.65      .1       0  244.97    .055       0   478.4    .045       0
   498.8    .055       0  545.92     .06       0  646.24     .05       0
  809.08     .06       0
#XS Ineff= 2 , 0
          465.99  1263.6  562.92          1263.3
Permanent Ineff=
       F       F
Bank Sta=478.4,498.8
XS Rating Curve= 0 ,0
Exp/Cntr(USF)=0,0
Exp/Cntr=0.5,0.3

Type RM Length L Ch R = 1 ,83      ,85.6,82.5,77.6
XS GIS Cut Line= 2
2467358.71527413673704.2189455872468286.64904449673664.728625248
#Sta/Elev= 30
       0  1298.6    20.5 1296.28    35.9 1300.43    48.1 1300.99    84.1 1298.47
  151.981296.347   204.2 1293.38   216.2 1290.92  243.181288.971     2521288.089
   288.3 1283.26   300.3 1276.86   304.3 1276.12  352.011272.083   412.4 1271.76
   419.9 1269.68   432.4 1263.31   460.4 1261.06   469.8 1257.53   476.5 1254.49
   484.5 1254.01   500.5 1254.53     512 1257.77  552.031257.911   696.7 1258.43
   812.8 1260.44   832.8    1263   844.8 1268.87   856.8 1271.67928.7737 1273.87
#Mann= 8 ,-1 , 0
       0     .06       0  151.98      .1       0  243.18     .06       0
     252    .055       0  352.01     .05       0   469.8    .045       0
     512     .05       0  552.03     .06       0
#XS Ineff= 2 , 0
                          761.27         1262.72
Permanent Ineff=
       F       F
Bank Sta=469.8,512
XS Rating Curve= 0 ,0
Exp/Cntr(USF)=0,0
Exp/Cntr=0.5,0.3

Type RM Length L Ch R = 1 ,0       ,,,
XS GIS Cut Line= 3
2467366.61293367673821.6782716892467589.80055687 673821.45841723
2468300.59228438673668.721803561
#Sta/Elev= 30
       0 1299.54   104.1 1286.89  164.011283.584   188.1  1282.5   210.7 1279.45
   273.3 1278.53     306 1275.06   314.2 1275.79  363.581273.032   387.8 1273.22
   461.4 1268.31   469.6 1265.76   473.7 1262.62   479.81255.619  479.83 1255.58
     486 1252.12   490.1 1252.03   506.5 1252.65   514.6 1255.45   522.8 1256.13
     531 1258.78   543.3 1257.54   580.1 1257.38  687.23 1259.01   727.4 1258.82
   837.8 1260.61   858.3 1269.39   870.6 1271.88   909.8 1273.69950.2045 1273.91
#Mann= 6 ,-1 , 0
       0      .1       0  164.01     .06       0  363.58     .05       0
  479.83    .045       0   514.6     .05       0  687.23     .06       0
#XS Ineff= 2 , 0
                          675.94         1263.51
Permanent Ineff=
       F       F
Bank Sta=479.8,514.6
XS Rating Curve= 0 ,0
Exp/Cntr(USF)=0,0
Exp/Cntr=0.3,0.1

River Reach=STONYCK_T1      ,Main
Reach XY= 19
     2464946.433       669040.33     2464974.866      669107.634
     2464996.509      669165.278     2465045.352      669258.954
     2465065.566      669297.477     2465122.612      669366.978
     2465146.592      669387.331      2465165.21      669417.147
     2465237.429      669460.848     2465275.912      669497.061
     2465383.519      669553.485      2465413.63      669570.464
     2465428.889      669593.282     2465462.317      669619.863
     2465488.985      669635.051     2465521.233       669681.06
      2465546.15      669697.087     2465579.158      669695.883
     2465610.547       669685.84

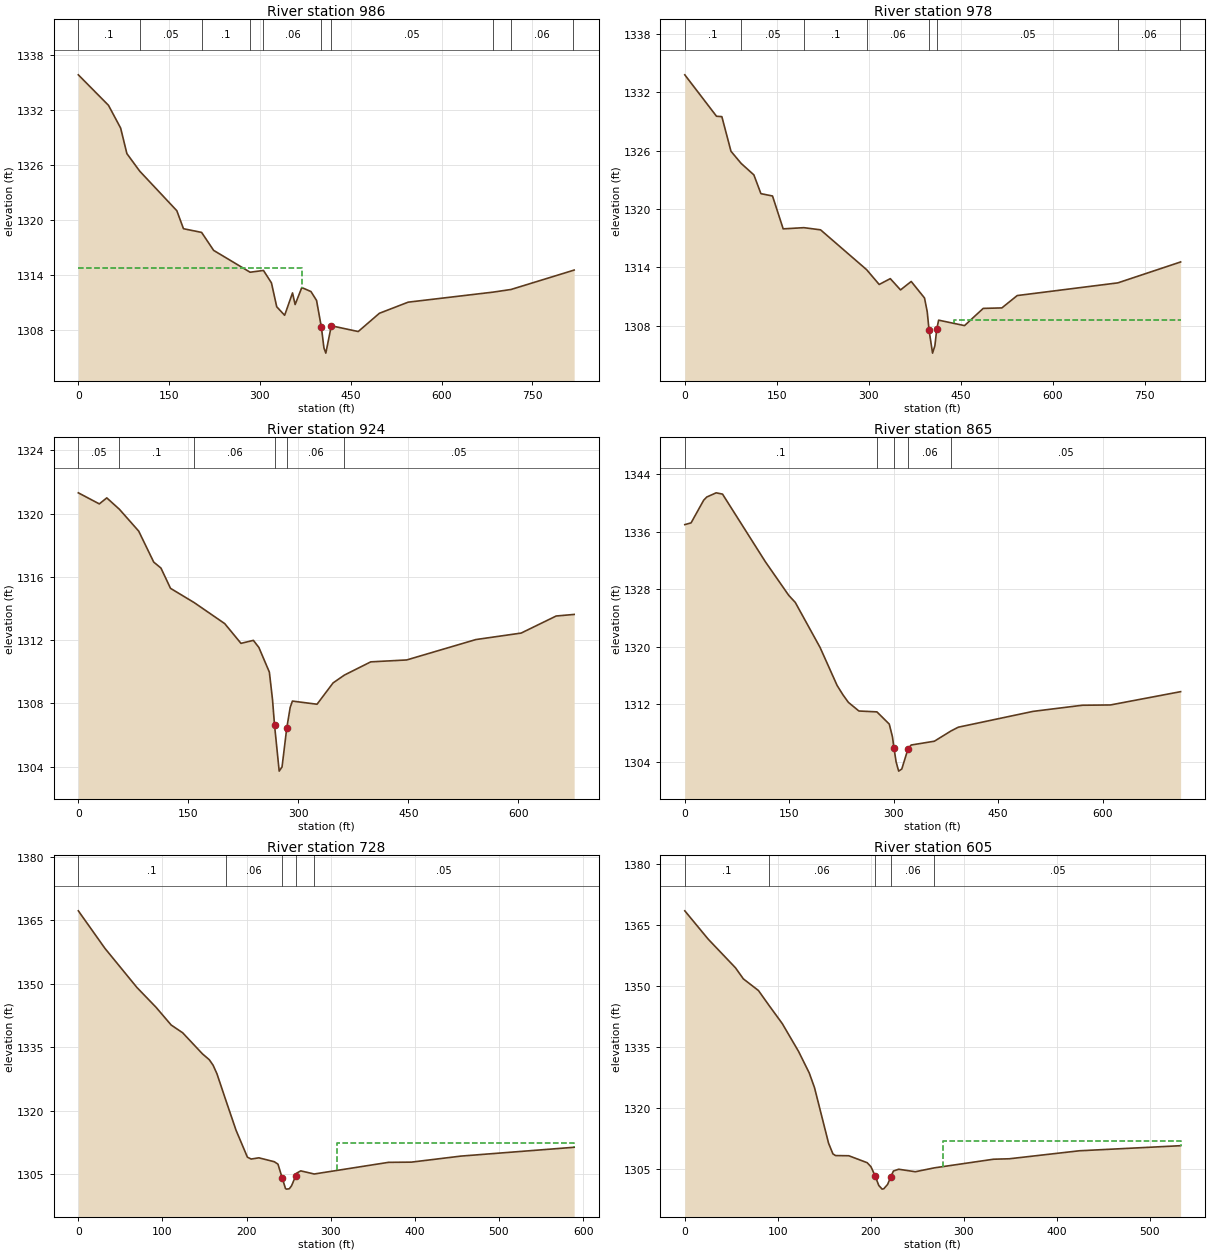
Type RM Length L Ch R = 1 ,986     ,8.8,7.9,7.9
XS GIS Cut Line= 3
2464568.84855392669200.6384870232464946.06855392669041.279487023
2465323.28855392668881.920487023
#Sta/Elev= 30
       0 1335.82    49.8  1332.5    69.9 1330.02    80.2 1327.24  101.391325.331
   162.7 1321.02   173.7 1319.06  203.611318.658   223.5  1316.7  283.761314.321
  305.831314.515     319 1313.16   327.7 1310.56   340.8 1309.63   353.8 1312.07
   358.1  1310.8   369.1 1312.65   384.2 1312.22   393.5 1311.25   401.5 1308.32
   405.7 1306.07   408.8 1305.51   417.9 1308.49   462.3 1307.86   497.3 1309.85
   544.8 1311.06  684.881312.152  714.711312.442  816.931314.513     819 1314.56
#Mann= 10 ,-1 , 0
       0      .1       0  101.39     .05       0  203.61      .1       0
  283.76     .05       0  305.83     .06       0   401.5    .045       0
   417.9     .05       0  684.88    .055       0  714.71     .06       0
  816.93     .05       0
#XS Ineff= 2 , 0
          368.77 1314.78
Permanent Ineff=
       F       F
Bank Sta=401.5,417.9
XS Rating Curve= 0 ,0
Exp/Cntr=0.3,0.1

Type RM Length L Ch R = 1 ,978     ,53.9,53.3,53.3
XS GIS Cut Line= 2
2464579.14089667669206.091907082 2465322.8804323668889.534576129
#Sta/Elev= 30
       0 1333.79    51.7 1329.53    60.4 1329.49    75.3 1325.93   91.891324.678
   112.6  1323.5   124.1 1321.57     143 1321.33   160.4 1317.95  194.171318.072
   221.3 1317.85  296.461313.749   316.9 1312.23     335 1312.83   351.7 1311.67
   369.1 1312.54   390.8 1310.84   395.2 1309.43   398.2 1307.53   403.9 1305.17
   407.7 1305.93   410.8 1307.65   413.8 1308.56     456    1308   486.5 1309.77
   516.9 1309.82   541.9 1311.09  705.971312.395   807.91314.537   808.3 1314.55
#Mann= 8 ,-1 , 0
       0      .1       0   91.89     .05       0  194.17      .1       0
  296.46     .06       0   398.2    .045       0   410.8     .05       0
  705.97     .06       0   807.9     .05       0
#XS Ineff= 2 , 0
                          438.79          1308.6
Permanent Ineff=
       F       F
Bank Sta=398.2,410.8
XS Rating Curve= 0 ,0
Exp/Cntr=0.3,0.1

Type RM Length L Ch R = 1 ,924     ,60.7,59.7,58.8
XS GIS Cut Line= 2
2464715.04414774669206.0632494142465337.26850787668941.545544688
#Sta/Elev= 30
       0 1321.32    28.6 1320.62    38.8    1321      56 1320.28    82.3  1318.9
   102.8 1316.94   112.7 1316.56   125.7 1315.28  158.271314.369   199.6 1313.05
   221.8  1311.8   238.7 1311.99   246.2 1311.54   260.5 1309.98   264.8 1308.24
   267.5 1306.65   273.9 1303.72   277.8 1303.99   284.2 1306.44   288.9 1307.75
   291.9 1308.15   325.5 1307.95   347.4  1309.3  362.831309.795   398.7 1310.63
   447.7 1310.75     542 1312.04   603.8 1312.45   651.6 1313.53   676.1 1313.63
#Mann= 6 ,-1 , 0
       0     .05       0      56      .1       0  158.27     .06       0
   267.5    .045       0   284.2     .06       0  362.83     .05       0
Bank Sta=267.5,284.2
XS Rating Curve= 0 ,0
Exp/Cntr=0.3,0.1

Type RM Length L Ch R = 1 ,865     ,136.8,136.6,136.3
XS GIS Cut Line= 3
2464718.79012886669296.7788489652464986.59903563669155.883420934
2465353.02103563668972.887420934
#Sta/Elev= 30
       0 1336.99       9 1337.23    27.1 1340.38    31.6 1340.83    45.1 1341.41
    54.2 1341.23   115.7 1331.83   149.4 1327.14   158.7 1326.17   194.3 1319.91
   218.8 1314.62   227.4 1313.29     235 1312.27   250.1 1311.07  275.95 1310.95
   293.7 1309.25   298.3 1307.47   300.5 1305.91   303.5 1304.01   307.2 1302.71
   311.7 1303.01   320.7 1305.83   325.1 1306.34   358.5 1306.87  382.471308.302
   392.9 1308.82   500.3 1311.02     571 1311.87   611.3 1311.91   712.2 1313.76
#Mann= 5 ,-1 , 0
       0      .1       0  275.95     .06       0   300.5    .045       0
   320.7     .06       0  382.47     .05       0
Bank Sta=300.5,320.7
XS Rating Curve= 0 ,0
Exp/Cntr=0.3,0.1

Type RM Length L Ch R = 1 ,728     ,125.8,122.9,119.3
XS GIS Cut Line= 2
2464833.24360775669392.1884499132465353.65469817   669115.573546
#Sta/Elev= 30
       0 1367.21    31.6 1358.36    69.6 1349.13    92.3 1344.46   110.4 1340.25
     124 1338.43   147.6 1333.44   155.7 1332.06   160.2 1330.77   164.8 1328.74
  175.461322.427   187.4 1315.46     201 1309.06   205.5 1308.62   214.6 1308.91
   232.9 1307.99   237.3 1307.42   242.2 1304.26   246.3 1301.64   247.6 1301.52
   250.8 1301.61   253.5 1302.33   258.4 1304.64   259.9 1305.34   264.4 1305.83
  280.36 1305.09   368.6 1307.84   395.8 1307.89     455 1309.32   589.4  1311.4
#Mann= 5 ,-1 , 0
       0      .1       0  175.46     .06       0   242.2    .045       0
   258.4     .06       0  280.36     .05       0
#XS Ineff= 2 , 0
                          307.06         1312.51
Permanent Ineff=
       F       F
Bank Sta=242.2,258.4
XS Rating Curve= 0 ,0
Exp/Cntr=0.3,0.1

Type RM Length L Ch R = 1 ,605     ,150.1,148.3,145.1
XS GIS Cut Line= 2
2464972.01989853669513.1488655232465367.56358317669155.633218525
#Sta/Elev= 30
       0  1368.4    25.2 1361.44    54.5 1354.42      63 1351.69    79.2 1348.84
   90.271345.281   104.8 1340.73   122.3 1333.91   133.8 1328.62   139.5 1324.99
   154.6 1311.37   159.3 1308.74   162.1 1308.33   176.4 1308.28   196.1 1306.58
   200.2 1305.59   204.6 1303.37   208.6    1301   212.2 1300.09     214 1300.18
   218.1 1301.25   221.6 1303.17   224.4 1304.54     230 1304.97   247.9 1304.36
  268.021305.298     332 1307.43     349 1307.54   424.2  1309.5   533.2 1310.75
#Mann= 5 ,-1 , 0
       0      .1       0   90.27     .06       0   204.6    .045       0
   221.6     .06       0  268.02     .05       0
#XS Ineff= 2 , 0
                          277.14         1311.98
Permanent Ineff=
       F       F
Bank Sta=204.6,221.6
XS Rating Curve= 0 ,0
Exp/Cntr=0.3,0.1

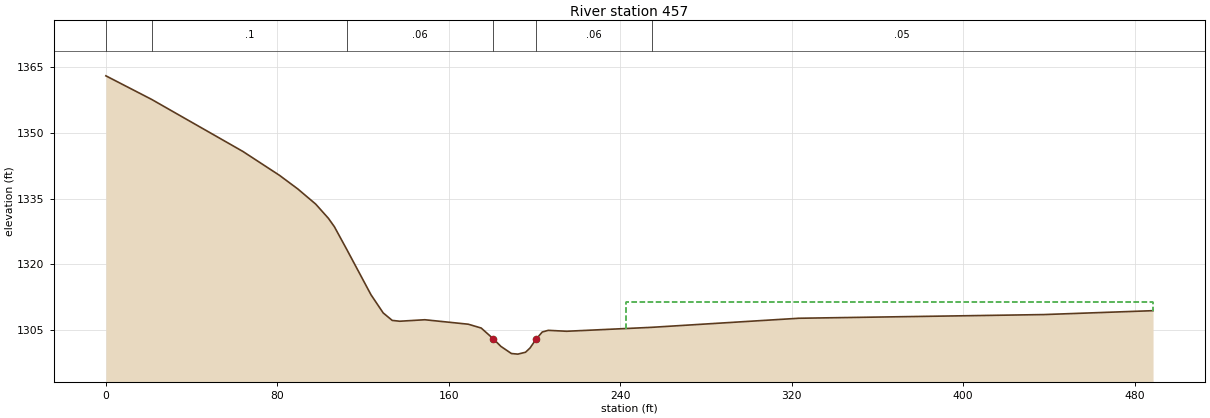
Type RM Length L Ch R = 1 ,457     ,132.6,131.2,130.5
XS GIS Cut Line= 2
2465122.66836587669616.4436830632465422.36506026669230.568110888
#Sta/Elev= 30
       0 1363.04   21.351357.653    63.9 1345.78      81 1340.32    89.5 1337.23
    97.9 1333.75   103.8 1330.52   106.6  1328.6  112.47 1323.33   123.7 1313.05
   129.4  1308.9   133.6  1307.2   137.1 1307.01   148.8 1307.35   169.1 1306.33
   175.1 1305.46   180.8 1302.98   184.3 1301.27   189.2 1299.64   192.2  1299.5
   195.8 1299.93   197.9  1300.9   200.7 1302.89   203.6 1304.55   206.4 1304.93
     215 1304.72   254.61305.616   323.3 1307.69   437.5 1308.53   488.6 1309.42
#Mann= 6 ,-1 , 0
       0      .1       0   21.35      .1       0  112.47     .06       0
   180.8    .045       0   200.7     .06       0   254.6     .05       0
#XS Ineff= 2 , 0
                          242.71         1311.29
Permanent Ineff=
       F       F
Bank Sta=180.8,200.7
XS Rating Curve= 0 ,0
Exp/Cntr=0.3,0.1