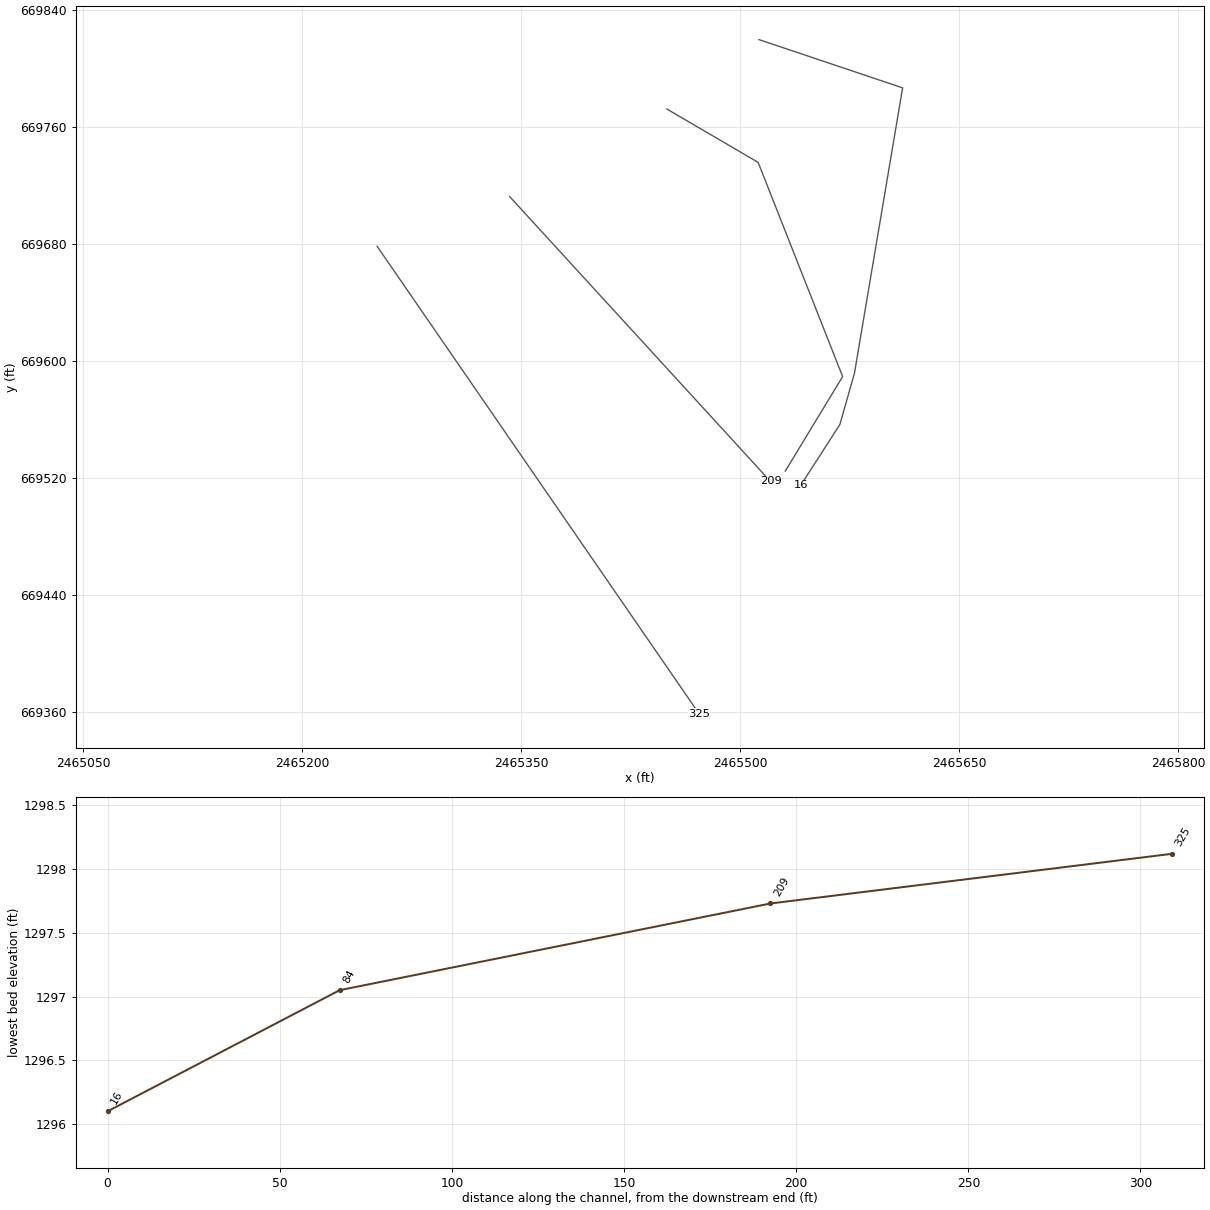
HEC-RAS study STONYCK_T1.prj: STONYCK_T1

--- STONYCK_T1.g01 (geometry) --- (continued)

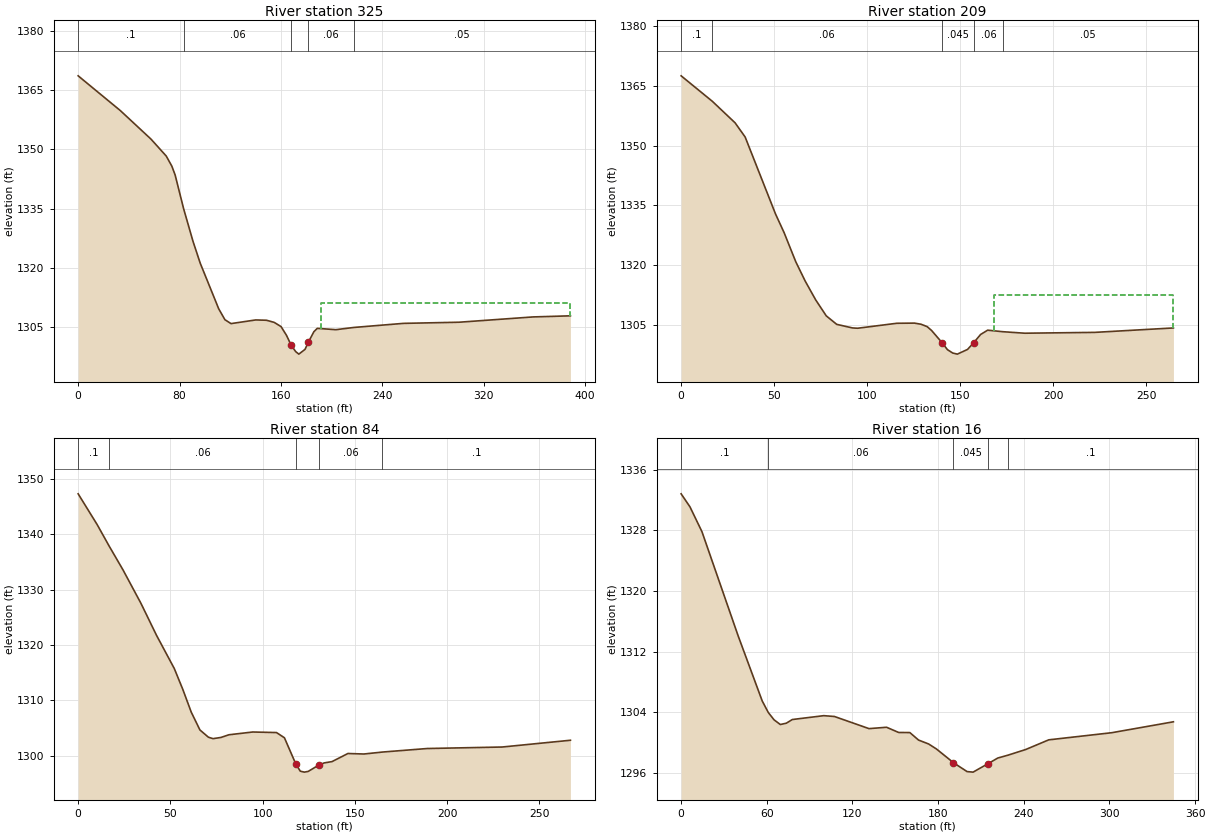
Type RM Length L Ch R = 1 ,325     ,114.8,116.7,118.3
XS GIS Cut Line= 2
2465251.29355659669678.1837746112465471.88575869 669358.55017566
#Sta/Elev= 30
       0 1368.61    33.2 1359.83    57.5 1352.57    69.5 1348.29    73.9 1345.75
    76.5 1343.52   83.181334.993    90.6 1326.71    96.3 1321.17   110.9  1309.6
   115.8 1306.84   120.6 1305.85   140.1 1306.78   148.6  1306.7   154.7 1306.16
   160.1 1305.09   164.4 1302.87     168 1300.44   171.6 1298.77   174.1 1298.12
     179 1299.32   181.6 1301.14     186  1303.8   188.7 1304.65   203.3 1304.31
  217.511304.877   256.7 1305.91   300.5  1306.2   358.8 1307.54   388.4 1307.82
#Mann= 5 ,-1 , 0
       0      .1       0   83.18     .06       0     168    .045       0
   181.6     .06       0  217.51     .05       0
#XS Ineff= 2 , 0
                          191.91         1310.99
Permanent Ineff=
       F       F
Bank Sta=168,181.6
XS Rating Curve= 0 ,0
Exp/Cntr=0.3,0.1

Type RM Length L Ch R = 1 ,209     ,128.7,125.1,120.6
XS GIS Cut Line= 2
2465341.97431606669712.2694501542465520.76333116669517.402286205
#Sta/Elev= 30
       0 1367.46   16.751361.083      29 1355.68    34.4 1352.13    50.7 1332.87
    55.3  1328.2    61.6 1320.88    66.6 1316.09    72.3 1311.32      78 1307.31
    83.6 1305.19    92.1 1304.29    94.9 1304.22   115.9 1305.46   125.4  1305.5
   128.9 1305.22   132.2 1304.62   134.6 1303.64   140.2  1300.6   143.1 1298.85
   145.9 1298.01   148.4 1297.73   153.9 1298.91   157.2 1300.59   160.9 1302.65
   164.7 1303.73  172.971303.343   184.6 1302.97   222.3 1303.18   264.5 1304.29
#Mann= 5 ,-1 , 0
       0      .1       0   16.75     .06       0   140.2    .045       0
   157.2     .06       0  172.97     .05       0
#XS Ineff= 2 , 0
                          167.92         1312.66
Permanent Ineff=
       F       F
Bank Sta=140.2,157.2
XS Rating Curve= 0 ,0
Exp/Cntr=0.3,0.1

Type RM Length L Ch R = 1 ,84      ,73.8,67.4,59.8
XS GIS Cut Line= 4
2465449.76222588669772.0158512452465512.27406857669735.550609675
 2465570.1554044669589.1108300342465530.88189579 669524.52149972
#Sta/Elev= 30
       0 1347.27    10.3 1341.72    16.7  1337.9    24.3 1333.55      34 1327.53
    42.5 1321.72    52.1 1315.75    56.7    1312    61.3 1307.87      66 1304.66
    70.6 1303.35    73.1 1303.09    77.4 1303.31    81.7 1303.79    94.6 1304.29
   107.5 1304.19   111.8 1303.25   117.9 1298.57   120.4 1297.22   122.6 1297.05
   124.7 1297.18   130.3  1298.3   133.3 1298.71   137.6 1298.95   146.2 1300.41
   154.9 1300.32  164.931300.673   189.2 1301.31   229.8 1301.58   266.8  1302.8
#Mann= 5 ,-1 , 0
       0      .1       0    16.7     .06       0   117.9    .045       0
   130.3     .06       0  164.93      .1       0
Bank Sta=117.9,130.3
XS Rating Curve= 0 ,0
Exp/Cntr=0.3,0.1

Type RM Length L Ch R = 1 ,16      ,,,
XS GIS Cut Line= 5
2465512.85288193669819.4785466232465611.25115284669786.486185202
2465578.25879142669591.4260834672465568.23847308669556.304999501
2465541.50539185669514.898103653
#Sta/Elev= 30
       0 1332.82     6.2  1331.1    14.6 1327.82      40 1314.05    56.8 1305.49
   61.031303.973    65.1    1303    69.5 1302.38    73.7 1302.56    77.9 1303.04
    99.9 1303.55   107.4 1303.44   131.6 1301.84   143.9 1302.02   152.4 1301.33
   160.2 1301.32   166.3 1300.33   173.3 1299.82   178.8 1299.16   190.6 1297.37
   190.6 1297.36   200.3 1296.17   204.5  1296.1   214.9 1297.21   221.8 1297.96
  228.921298.336   241.3 1299.08   257.5 1300.36   301.6  1301.3   344.8 1302.74
#Mann= 5 ,-1 , 0
       0      .1       0   61.03     .06       0   190.6    .045       0
   214.9     .06       0  228.92      .1       0
Bank Sta=190.6,214.9
XS Rating Curve= 0 ,0
Exp/Cntr=0.3,0.1
LCMann Table=0

Chan Stop Cuts=-1
Use User Specified Reach Order=0
Composite Channel Slope=5